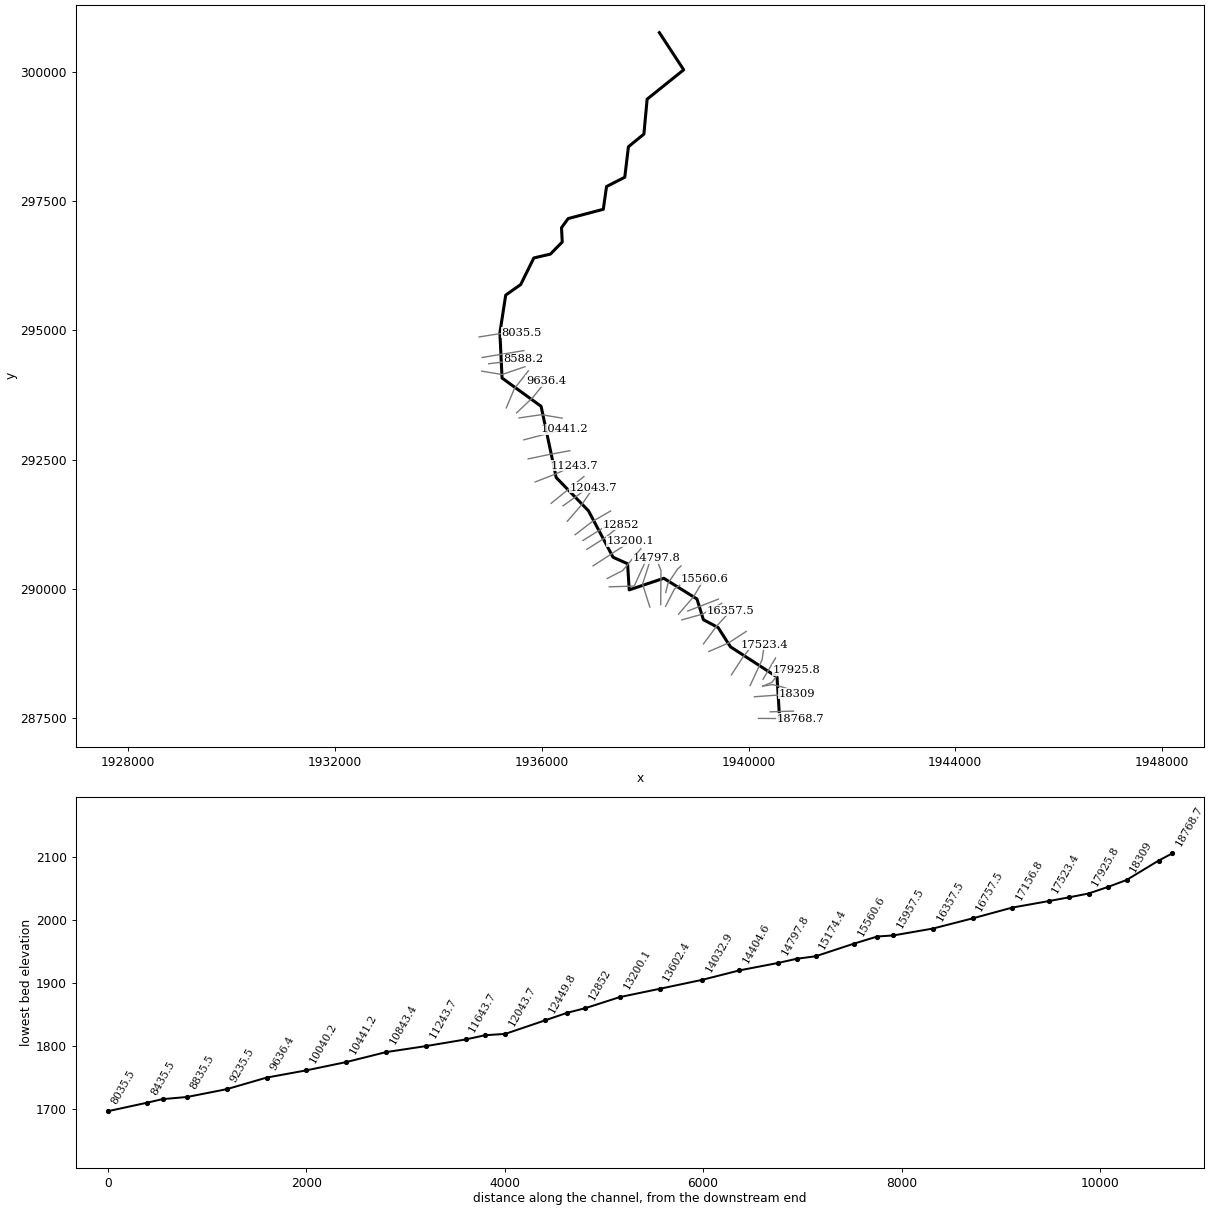
--- FtCrk.prj (project) ---

Proj Title=FtCrk
Current Plan=p01
Geom File=g01
Flow File=f01
Plan File=p01
DSS Export Rating Curves=0
DSS Export Rating Curve Sorted=0
DSS Export Volume Flow Curves=0
DXF OffsetX=0
DXF OffsetY=0
DXF ScaleX=0
DXF ScaleY=0

--- FtCrk.p01 (plan) ---

Plan Title=Floodplain
Program Version=4.00
Geom File=g01
Flow File=f01
K Sum by GR=0
Std Step Tol=0.01
Critical Tol=0.01
Num of Std Step Trials=20
Max Error Tol=0.3
Flow Tol Ratio=0.001
Split Flow NTrial=30
Split Flow Tol=0.02
Split Flow Ratio=0.02
Log Output Level=0
Friction Slope Method=1
Unsteady Friction Slope Method=2
Unsteady Bridges Friction Slope Method=1
Global Log Level=0
CheckData=False
Run HTab=0
Run UNet=0
Run PostProcess=0
UNET Theta=0
UNET Theta Warmup=0
UNET ZTol=0
UNET ZSATol=0
UNET MxIter=0
UNET MaxInSteps=0
UNET DtIC=0
UNET DtMin=0
UNET MaxCRTS=0
UNET WFStab=0
UNET SFStab=0
UNET WFX=0
UNET SFX=0
UNET DSS MLevel=0
UNET DZMax Abort=0
UNET Convert EG Bridges=0
UNET Use Existing IB Tables=0
UNET Froude Limit=0
UNET Froude Power=0
Write IC File=0
Echo Input=False
Echo Output=False
Write Detailed=0

--- FtCrk.f01 (steady flow) ---

Flow Title=NFF Regression Equation
Program Version=4.00
Number of Profiles=1
Profile Names=P100yr
River Rch & RM=FtCrk,Main      ,18768.7
515.0376
River Rch & RM=FtCrk,Main      ,18121.3
519.1744
River Rch & RM=FtCrk,Main      ,17925.8
878.6620
River Rch & RM=FtCrk,Main      ,15174.4
911.1236
River Rch & RM=FtCrk,Main      ,14797.8
1012.095
River Rch & RM=FtCrk,Main      ,14032.9
1411.972
River Rch & RM=FtCrk,Main      ,14032.9
1015.591
River Rch & RM=FtCrk,Main      ,9636.4
1493.456
River Rch & RM=FtCrk,Main      ,1148.1
1656.308
River Rch & RM=FtCrk,Main      ,849.8
1851.422
River Rch & RM=FtCrk,Main      ,147.9
1852.926
Boundary for River Rch & Prof#=FtCrk,Main      ,1
Up Type=0
Dn Type=3
Dn Slope=0.058174

--- FtCrk.g01 (geometry) ---

Geom Title=USGS 3m DEM
Program Version=4.00

River Reach=FtCrk     ,Main
Reach XY= 30
     1940602.474      287481.821     1940551.522      288296.070
     1939651.027      288879.255     1939412.745      289251.651
     1939127.589      289403.995     1939002.589      289805.037
     1938361.344      290204.983     1937692.693      289980.818
     1937660.946      290485.778     1937380.293      290611.678
     1936904.232      291510.687     1936279.933      292153.995
     1935988.266      293531.599     1935232.756      294078.514
     1935191.118      294952.425     1935303.370      295682.641
     1935593.735      295887.068     1935847.641      296401.390
     1936167.954      296475.609     1936397.121      296709.984
     1936382.797      296987.328     1936511.704      297163.109
     1937191.391      297342.797     1937253.891      297782.901
     1937606.756      297962.588     1937677.068      298552.432
     1937976.547      298797.224     1938039.047      299473.005
     1938746.079      300040.714     1938276.061      300759.535

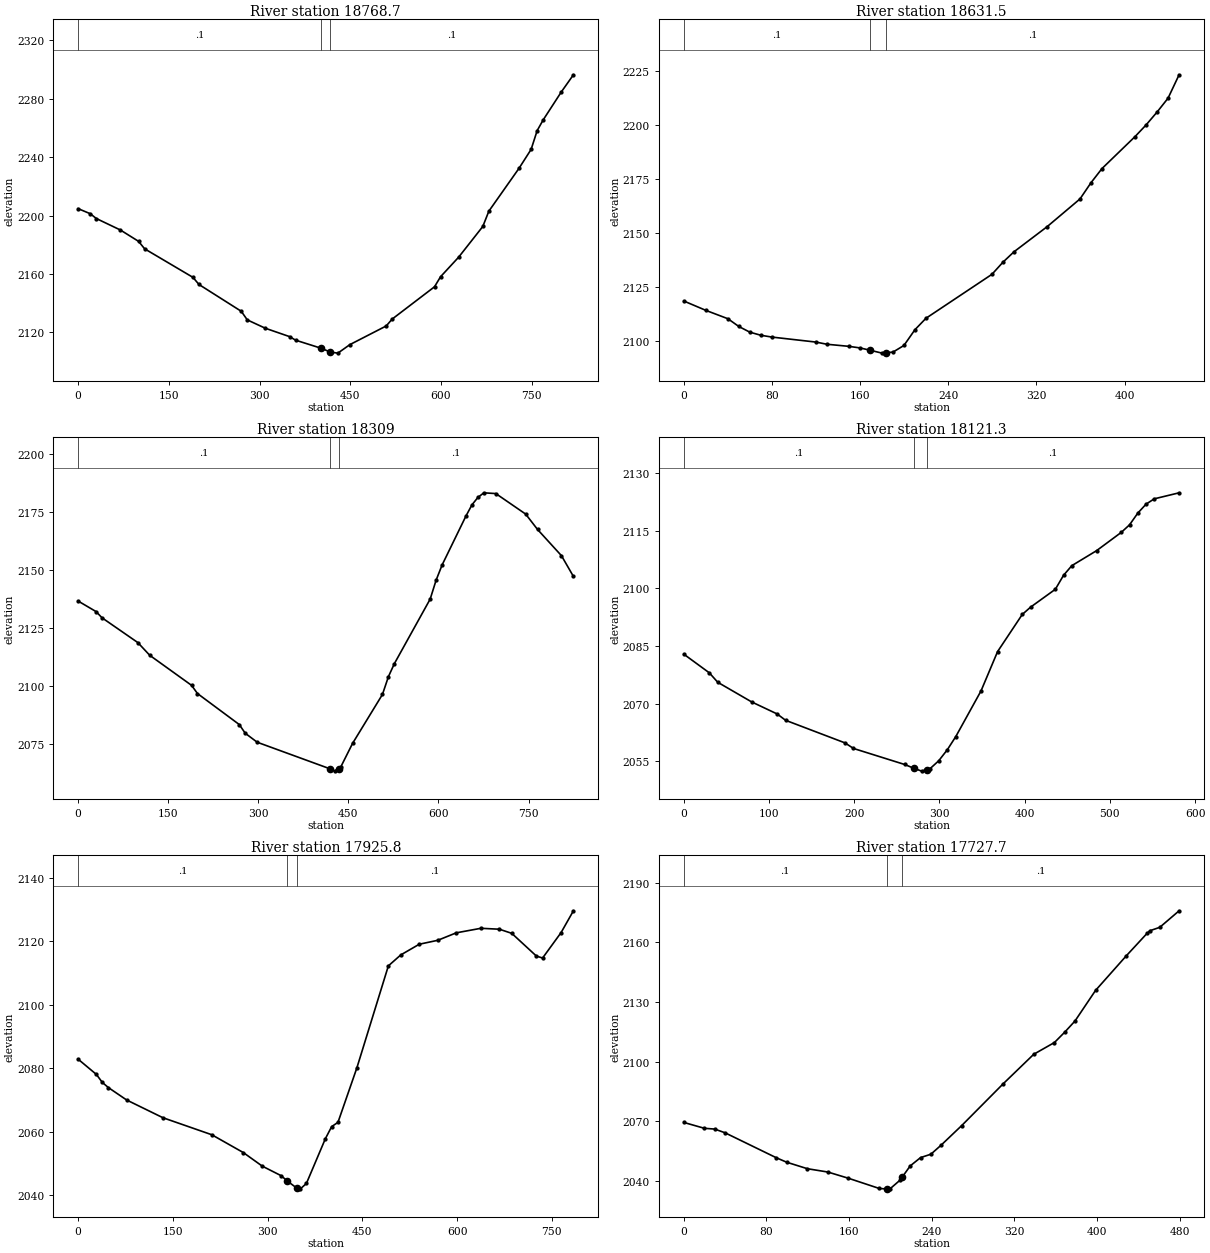
Type RM Length L Ch R = 1 ,18768.7,136.4,137.3,138.2
XS GIS Cut Line= 3
     1940193.050      287494.551     1940602.541      287491.820
     1941012.032      287489.090
#Sta/Elev= 30
       0 2204.73    20.0 2201.26    30.0 2197.98    69.9 2190.09    99.9 2182.34
   109.9 2177.23   189.8 2157.68   199.8 2152.79   269.7 2134.44   279.7 2128.54
   309.6 2122.81   349.6 2117.09   359.6 2114.65     402 2109.10     417 2106.50
   429.5 2105.78   449.4 2111.62   509.4 2124.38   519.4 2129.14   589.3 2151.22
   599.3 2158.10   629.2 2171.49   669.2 2192.54   679.2 2203.03   729.1 2232.39
   749.1 2245.34   759.1 2258.21   769.1 2265.57   799.0 2284.67   819.0 2296.40
#Mann= 3 , 0 , 0
       0     0.1       0     402   0.045       0     417     0.1       0
Bank Sta=     402,     417
Exp/Cntr=0.3,0.1

Type RM Length L Ch R = 1 ,18631.5,321.4,322.4,323.3
XS GIS Cut Line= 2
     1940419.895      287621.529     1940869.057      287636.112
#Sta/Elev= 30
       0 2118.44    20.0 2114.11    40.0 2110.24    49.9 2106.65    59.9 2104.02
    69.9 2102.59    79.9 2101.75   119.8 2099.44   129.8 2098.43   149.8 2097.46
   159.8 2096.73   168.7 2095.70   179.8 2094.32   183.7 2094.51   189.8 2094.80
   199.7 2097.86   209.7 2105.16   219.7 2110.45   279.6 2130.81   289.6 2136.43
   299.6 2141.24   329.6 2152.84   359.5 2165.71   369.5 2173.23   379.5 2179.80
   409.4 2194.55   419.4 2199.93   429.4 2205.91   439.4 2212.36   449.4 2223.17
#Mann= 3 , 0 , 0
       0     0.1       0   168.7   0.045       0   183.7     0.1       0
Bank Sta=   168.7,   183.7
Exp/Cntr=0.3,0.1

Type RM Length L Ch R = 1 ,18309,194.4,187.6,180.8
XS GIS Cut Line= 2
     1940115.106      287913.193     1940937.598      287972.984
#Sta/Elev= 30
       0 2136.72    29.8 2132.19    39.7 2129.52    99.4 2118.84   119.2 2113.37
   188.8 2100.45   198.7 2096.91   268.3 2083.56   278.2 2079.83   298.1 2075.96
   418.7 2064.58   427.2 2063.52   433.7 2064.65   437.2 2065.26   457.0 2075.48
   506.7 2096.52   516.7 2104.21   526.6 2109.80   586.2 2137.58   596.1 2145.73
   606.1 2152.28   645.8 2173.34   655.8 2178.15   665.7 2181.34   675.6 2183.31
   695.5 2182.99   745.2 2174.16   765.0 2167.54   804.8 2156.26   824.7 2147.34
#Mann= 3 , 0 , 0
       0     0.1       0   418.7   0.045       0   433.7     0.1       0
Bank Sta=   418.7,   433.7
Exp/Cntr=0.3,0.1

Type RM Length L Ch R = 1 ,18121.3,169.1,195.6,222.1
XS GIS Cut Line= 4
     1940275.278      288119.560     1940462.176      288148.225
     1940608.352      288114.214     1940840.044      288044.269
#Sta/Elev= 30
       0 2082.88    29.9 2078.03    39.8 2075.57    79.6 2070.46   109.5 2067.33
   119.4 2065.68   189.1 2059.80   199.1 2058.35   259.1 2054.18   270.4 2053.16
   279.1 2052.45   285.4 2052.87   289.1 2053.12   299.1 2055.14   309.2 2058.01
   319.2 2061.46   348.8 2073.34   368.2 2083.56   397.2 2093.23   406.9 2095.12
   436.0 2099.78   445.6 2103.41   455.3 2105.92   484.4 2109.83   513.4 2114.59
   523.1 2116.56   532.8 2119.61   542.5 2121.94   552.1 2123.32   581.2 2124.88
#Mann= 3 , 0 , 0
       0     0.1       0   270.4   0.045       0   285.4     0.1       0
Bank Sta=   270.4,   285.4
Exp/Cntr=0.3,0.1

Type RM Length L Ch R = 1 ,17925.8,195.3,197.6,199.8
XS GIS Cut Line= 4
     1940275.278      288119.560     1940453.436      288190.274
     1940630.021      288432.261     1940923.015      288430.896
#Sta/Elev= 30
       0 2082.88    28.8 2078.10    38.3 2075.56    47.9 2073.94    76.7 2070.05
   134.2 2064.46   211.6 2059.10   261.6 2053.48   291.5 2049.22   321.5 2046.20
     331 2044.56     346 2042.33   351.4 2041.98   361.4 2043.76   391.4 2057.84
   401.4 2061.66   411.4 2063.01   441.3 2080.14   491.2 2112.27   510.8 2115.71
   540.1 2119.08   569.4 2120.32   598.7 2122.67   637.7 2124.10   667.0 2123.81
   686.6 2122.51   725.6 2115.36   735.4 2114.74   764.7 2122.75   784.2 2129.60
#Mann= 3 , 0 , 0
       0     0.1       0     331   0.045       0     346     0.1       0
Bank Sta=     331,     346
Exp/Cntr=0.3,0.1

Type RM Length L Ch R = 1 ,17727.7,202,204.2,206.4
XS GIS Cut Line= 4
     1940281.354      288251.523     1940508.852      288637.978
     1940511.769      288637.978     1940521.977      288664.228
#Sta/Elev= 30
       0 2069.42    19.9 2066.47    29.9 2066.08    39.9 2064.21    89.7 2051.62
    99.6 2049.41   119.6 2046.15   139.5 2044.47   159.4 2041.34   189.3 2036.20
   196.4 2035.97   199.3 2035.88   209.3 2040.38   211.4 2041.91   219.2 2047.57
   229.2 2051.74   239.2 2053.44   249.1 2057.99   269.1 2067.88   308.9 2088.71
   338.8 2103.71   358.8 2109.61   368.7 2114.78   378.7 2120.42   398.6 2135.80
   428.5 2153.28   448.4 2164.45   451.4 2165.87   460.8 2167.55   479.5 2175.85
#Mann= 3 , 0 , 0
       0     0.1       0   196.4   0.045       0   211.4     0.1       0
Bank Sta=   196.4,   211.4
Exp/Cntr=0.3,0.1

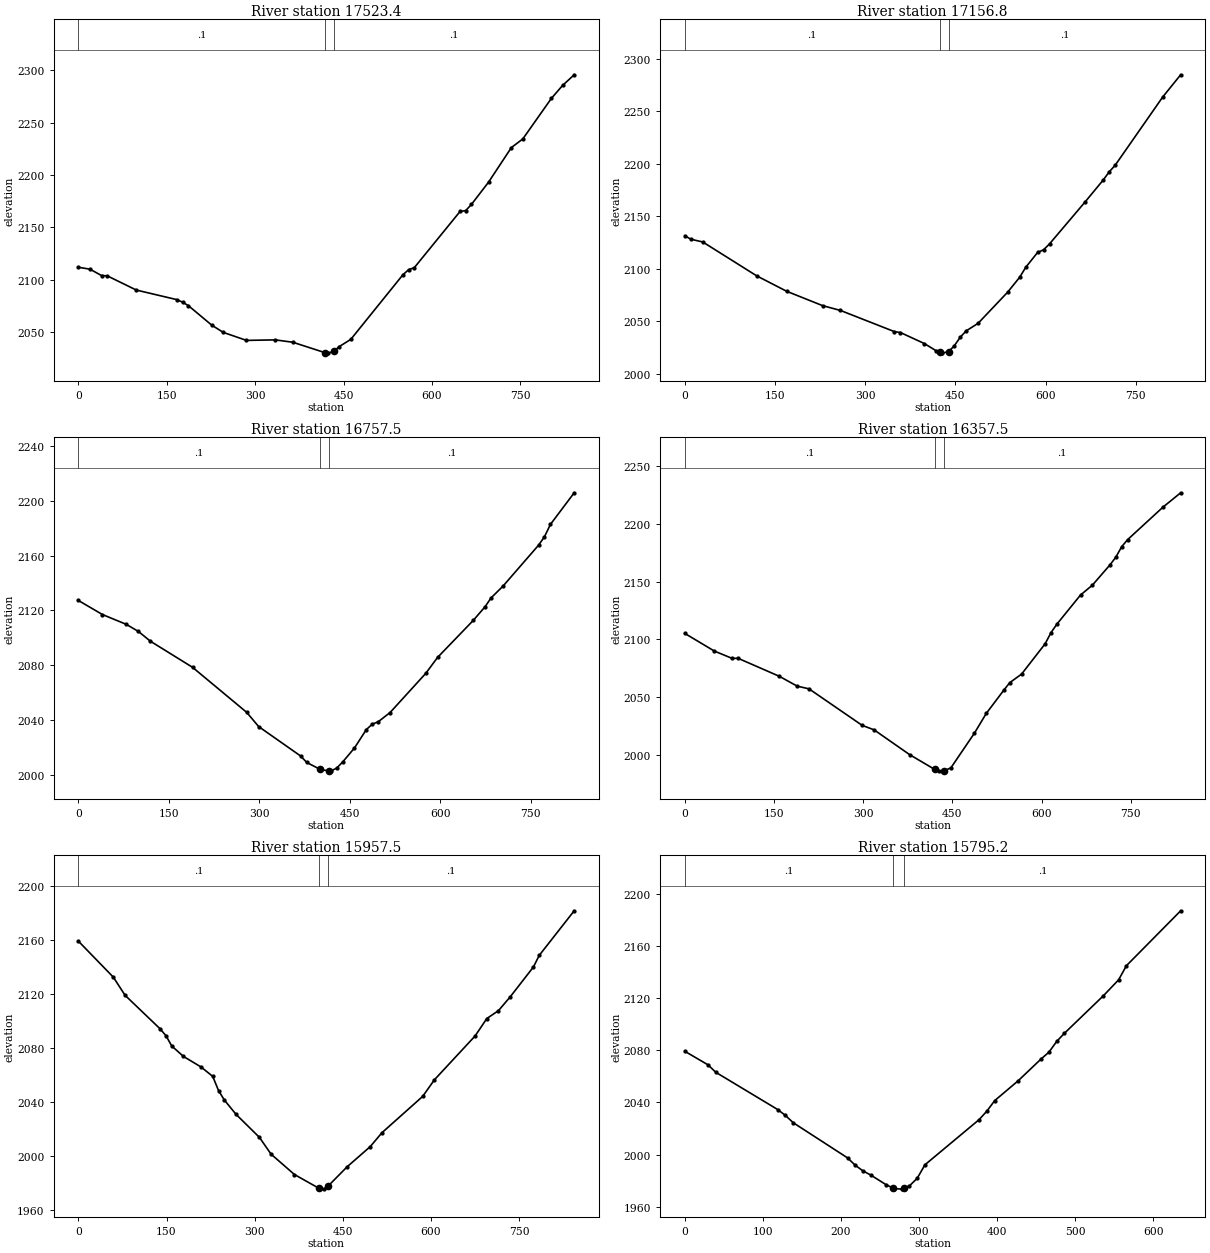
Type RM Length L Ch R = 1 ,17523.4,371.7,366.7,361.6
XS GIS Cut Line= 3
     1940032.097      288131.184     1940263.854      288630.686
     1940303.942      288918.331
#Sta/Elev= 30
       0 2111.95    19.7 2110.11    39.3 2104.04    49.2 2103.71    98.3 2090.18
   167.2 2081.01   177.0 2078.55   186.8 2075.24   226.2 2056.70   245.8 2049.75
   285.2 2042.09   334.3 2042.58   363.8 2040.32   418.3 2030.39   422.8 2029.93
   433.3 2031.52   442.5 2036.13   462.2 2043.08   550.6 2104.78   560.3 2109.62
   570.0 2111.61   647.5 2165.21   657.1 2166.06   666.8 2171.92   695.9 2193.24
   734.6 2226.26   754.0 2234.51   802.4 2273.18   821.7 2285.76   841.1 2295.74
#Mann= 3 , 0 , 0
       0     0.1       0   418.3   0.045       0   433.3     0.1       0
Bank Sta=   418.3,   433.3
Exp/Cntr=0.3,0.1

Type RM Length L Ch R = 1 ,17156.8,410.1,398.9,391.6
XS GIS Cut Line= 3
     1939668.541      288336.359     1939891.598      288678.373
     1940151.063      289003.756
#Sta/Elev= 30
       0 2131.45    10.0 2128.15    29.9 2125.51   119.5 2093.27   169.3 2078.57
   229.1 2064.88   258.9 2060.29   348.6 2040.11   358.5 2039.28   398.4 2028.75
   418.2 2021.80   423.8 2020.58   428.1 2019.64   438.8 2021.16   448.0 2026.48
   457.9 2034.70   467.8 2040.80   487.6 2047.98   537.1 2077.86   557.0 2092.02
   566.9 2101.35   586.7 2115.57   596.6 2118.07   606.5 2123.69   666.0 2163.90
   695.7 2184.50   705.6 2192.21   715.5 2198.50   794.8 2263.68   824.5 2284.74
#Mann= 3 , 0 , 0
       0     0.1       0   423.8   0.045       0   438.8     0.1       0
Bank Sta=   423.8,   438.8
Exp/Cntr=0.3,0.1

Type RM Length L Ch R = 1 ,16757.5,388.2,400,405.6
XS GIS Cut Line= 3
     1939233.661      288788.914     1939608.900      288951.148
     1939955.515      289176.708
#Sta/Elev= 30
       0 2127.24    39.9 2116.96    79.8 2109.72    99.7 2104.56   119.6 2097.42
   189.4 2078.38   279.2 2045.48   299.1 2035.06   368.9 2013.49   378.9 2008.82
   401.3 2003.74   416.3 2002.53   418.6 2002.50   428.5 2004.73   438.4 2009.15
   458.0 2019.42   477.7 2032.87   487.6 2036.84   497.4 2038.57   517.1 2045.33
   576.2 2073.91   595.9 2085.63   655.0 2112.62   674.7 2122.67   684.5 2129.07
   704.2 2137.61   763.3 2167.60   773.1 2173.74   783.0 2182.79   822.4 2205.89
#Mann= 3 , 0 , 0
       0     0.1       0   401.3   0.045       0   416.3     0.1       0
Bank Sta=   401.3,   416.3
Exp/Cntr=0.3,0.1

Type RM Length L Ch R = 1 ,16357.5,415.2,400,392.9
XS GIS Cut Line= 3
     1939128.329      288935.249     1939383.028      289278.892
     1939657.563      289578.383
#Sta/Elev= 30
       0 2105.22    49.7 2089.98    79.6 2083.66    89.5 2083.76   159.2 2068.14
   189.0 2059.70   208.9 2057.36   298.4 2025.79   318.3 2021.98   378.0 2000.60
   420.2 1987.82   427.7 1986.30   435.2 1986.38   447.6 1989.15   487.2 2019.13
   507.0 2036.07   536.7 2056.28   546.6 2062.70   566.5 2070.11   606.1 2096.25
   616.0 2105.93   625.9 2113.24   665.6 2138.37   685.4 2146.79   715.1 2164.35
   725.0 2171.05   734.9 2180.11   744.8 2186.18   804.3 2214.25   834.0 2226.62
#Mann= 3 , 0 , 0
       0     0.1       0   420.2   0.045       0   435.2     0.1       0
Bank Sta=   420.2,   435.2
Exp/Cntr=0.3,0.1

Type RM Length L Ch R = 1 ,15957.5,159.9,162.2,158.7
XS GIS Cut Line= 3
     1938709.900      289400.467     1939112.036      289512.223
     1939483.022      289721.917
#Sta/Elev= 30
       0 2159.24    59.6 2132.46    79.5 2119.06   139.1 2094.19   149.1 2089.06
   159.0 2081.41   178.9 2073.70   208.7 2065.91   228.6 2058.94   238.5 2048.43
   248.4 2041.38   268.3 2030.78   308.1 2013.69   327.9 2001.25   367.7 1986.14
   409.9 1975.82   417.4 1975.33   424.9 1977.59   457.0 1991.78   496.7 2006.89
   516.5 2017.15   585.8 2044.08   605.7 2056.36   675.0 2088.90   694.9 2101.82
   714.7 2107.66   734.5 2117.78   774.2 2140.04   784.1 2148.66   843.5 2181.68
#Mann= 3 , 0 , 0
       0     0.1       0   409.9   0.045       0   424.9     0.1       0
Bank Sta=   409.9,   424.9
Exp/Cntr=0.3,0.1

Type RM Length L Ch R = 1 ,15795.2,223.5,234.7,249.9
XS GIS Cut Line= 2
     1938824.492      289571.303     1939416.570      289801.717
#Sta/Elev= 30
       0 2079.21    29.8 2068.79    39.7 2063.11   119.1 2034.55   129.0 2030.02
   139.0 2024.45   208.5 1997.55   218.4 1991.90   228.3 1987.56   238.2 1984.42
   258.1 1976.93   266.4 1974.53   268.0 1974.07   278.0 1973.61   281.4 1974.48
   287.9 1976.14   297.8 1981.92   307.7 1992.25   377.2 2026.90   387.2 2033.50
   397.1 2041.42   426.9 2056.48   456.6 2073.36   466.6 2078.54   476.5 2086.75
   486.4 2092.99   536.1 2121.60   555.9 2133.96   565.8 2144.73   635.3 2186.79
#Mann= 3 , 0 , 0
       0     0.1       0   266.4   0.045       0   281.4     0.1       0
Bank Sta=   266.4,   281.4
Exp/Cntr=0.3,0.1

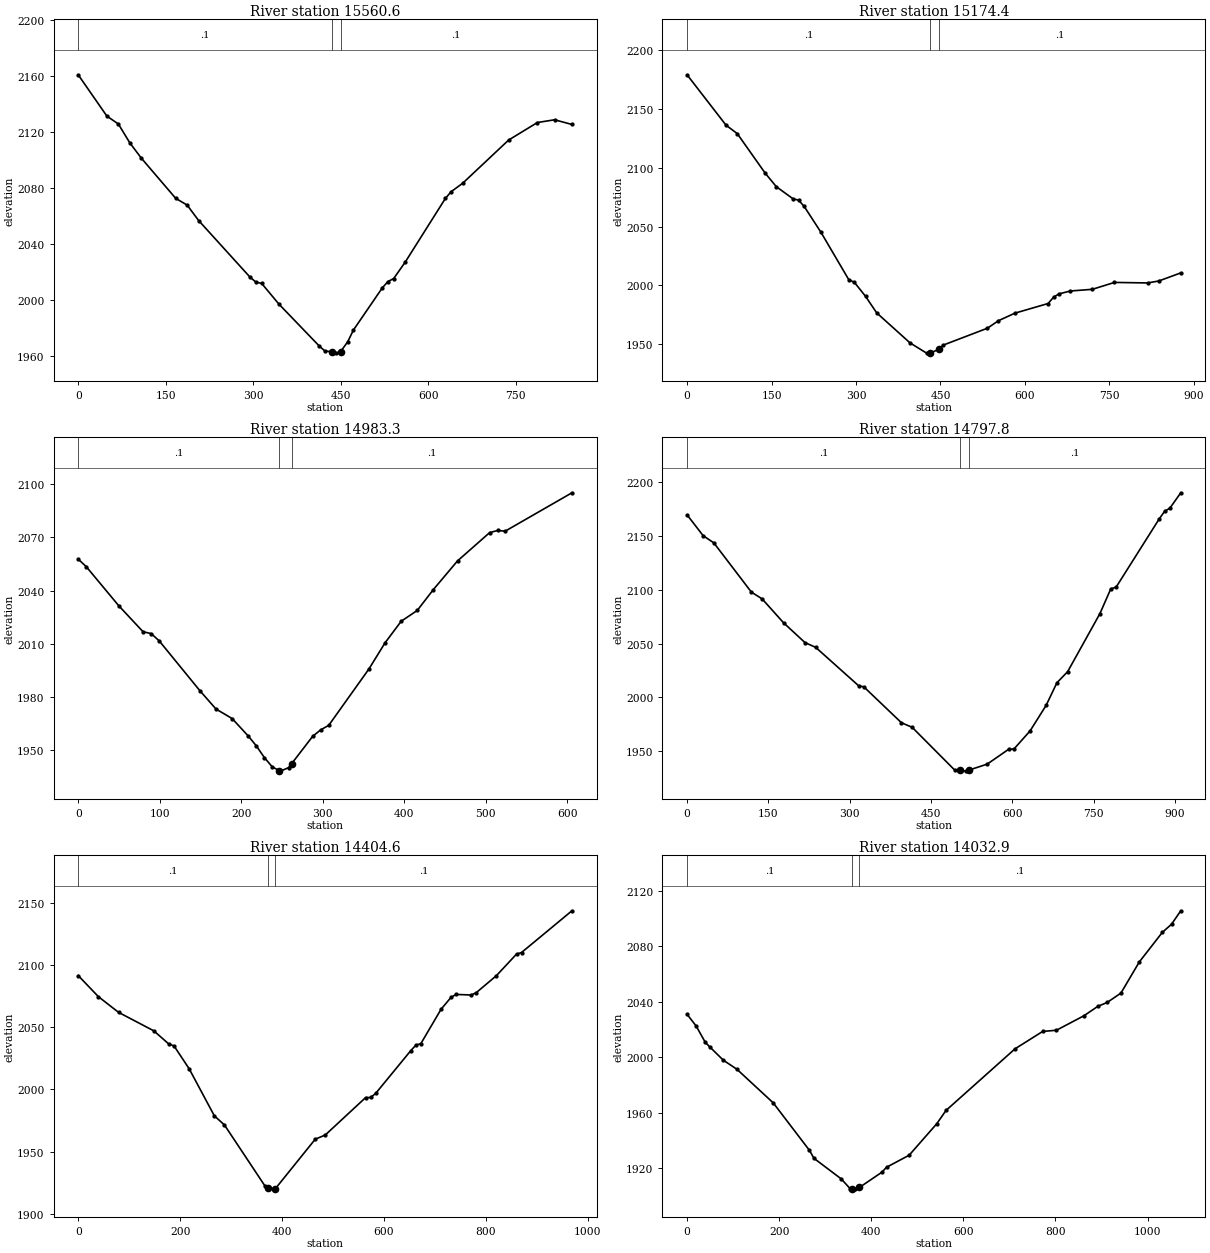
Type RM Length L Ch R = 1 ,15560.6,391.2,386.1,376.9
XS GIS Cut Line= 3
     1938646.332      289510.397     1938935.476      289844.849
     1939141.467      290192.092
#Sta/Elev= 30
       0 2160.96    49.1 2131.49    68.8 2125.84    88.4 2112.40   108.1 2101.48
   167.0 2072.78   186.7 2067.92   206.3 2056.94   294.7 2016.35   304.6 2012.94
   314.4 2011.99   343.9 1997.24   412.6 1967.49   422.5 1963.84   434.6 1963.10
   442.1 1962.24   449.6 1963.32   461.8 1970.36   471.6 1978.75   520.9 2008.74
   530.7 2013.34   540.6 2015.52   560.3 2027.22   629.2 2072.74   639.1 2077.54
   658.8 2083.55   737.5 2114.38   786.8 2126.90   816.3 2128.86   845.9 2125.53
#Mann= 3 , 0 , 0
       0     0.1       0   434.6   0.045       0   449.6     0.1       0
Bank Sta=   434.6,   449.6
Exp/Cntr=0.3,0.1

Type RM Length L Ch R = 1 ,15174.4,183,191,199
XS GIS Cut Line= 3
     1938396.155      289662.515     1938567.714      289997.476
     1938971.051      290293.780
#Sta/Elev= 30
       0 2179.27    69.3 2136.30    89.1 2129.22   138.6 2095.58   158.5 2083.98
   188.2 2073.66   198.1 2072.49   208.0 2067.15   237.7 2045.20   287.2 2004.76
   297.1 2002.52   316.9 1990.64   336.7 1976.52   396.0 1950.91   425.4 1942.19
   431.6 1942.25   446.6 1945.29   454.8 1948.99   533.4 1963.41   553.0 1969.80
   582.4 1976.26   641.3 1984.46   651.1 1989.96   660.9 1992.70   680.6 1995.10
   719.8 1996.56   759.1 2002.42   817.9 2001.98   837.6 2003.62   876.8 2010.52
#Mann= 3 , 0 , 0
       0     0.1       0   431.6   0.045       0   446.6     0.1       0
Bank Sta=   431.6,   446.6
Exp/Cntr=0.3,0.1

Type RM Length L Ch R = 1 ,14983.3,172.5,185.1,197.8
XS GIS Cut Line= 4
     1938398.663      289930.050     1938442.413      290103.590
     1938627.619      290383.587     1938696.160      290443.378
#Sta/Elev= 30
       0 2057.71     9.9 2053.46    49.7 2031.46    79.5 2016.79    89.5 2015.73
    99.4 2011.60   149.1 1983.61   169.0 1973.19   188.8 1967.82   208.6 1957.96
   218.5 1952.40   228.3 1945.84   238.2 1940.47   246.8 1938.46   248.1 1938.16
   258.0 1940.12   261.8 1942.35   287.6 1957.78   297.5 1961.46   307.3 1963.97
   356.7 1995.82   376.4 2010.53   396.2 2022.69   415.9 2028.78   435.7 2040.58
   465.3 2056.73   504.8 2072.72   514.7 2073.89   523.8 2073.51   605.6 2095.13
#Mann= 3 , 0 , 0
       0     0.1       0   246.8   0.045       0   261.8     0.1       0
Bank Sta=   246.8,   261.8
Exp/Cntr=0.3,0.1

Type RM Length L Ch R = 1 ,14797.8,386,393.2,400.5
XS GIS Cut Line= 3
     1938302.007      289695.023     1938306.789      290357.337
     1938215.854      290588.318
#Sta/Elev= 30
       0 2169.54    29.7 2150.19    49.4 2143.53   118.6 2097.84   138.4 2091.56
   177.9 2069.38   217.5 2050.96   237.2 2046.56   316.3 2010.96   326.2 2009.80
   395.4 1976.55   415.2 1972.31   494.3 1932.27   504.3 1932.23   514.0 1931.63
   519.3 1932.48   553.6 1938.13   593.1 1951.90   603.0 1952.19   632.7 1968.97
   662.3 1992.68   682.2 2013.68   702.0 2023.98   761.6 2077.94   781.5 2100.78
   791.4 2102.44   870.8 2165.71   880.8 2172.83   890.7 2175.84   910.6 2190.01
#Mann= 3 , 0 , 0
       0     0.1       0   504.3   0.045       0   519.3     0.1       0
Bank Sta=   504.3,   519.3
Exp/Cntr=0.3,0.1

Type RM Length L Ch R = 1 ,14404.6,413.7,371,328.4
XS GIS Cut Line= 3
     1938091.122      289649.648     1937950.959      290093.382
     1938106.028      290572.741
#Sta/Elev= 30
       0 2091.82    39.6 2074.81    79.2 2062.16   148.5 2047.24   178.2 2036.53
   188.1 2035.11   217.8 2016.68   267.3 1978.71   287.1 1971.39   366.3 1922.41
   372.2 1920.82   386.1 1919.67   387.2 1920.11   465.3 1959.90   485.1 1963.32
   564.1 1993.41   574.0 1993.55   583.9 1996.79   653.0 2031.35   662.9 2035.72
   672.8 2037.01   712.3 2064.61   732.1 2074.34   742.0 2076.60   771.6 2076.16
   781.5 2078.05   821.0 2091.73   860.5 2109.10   870.4 2110.40   969.2 2144.00
#Mann= 3 , 0 , 0
       0     0.1       0   372.2   0.045       0   387.2     0.1       0
Bank Sta=   372.2,   387.2
Exp/Cntr=0.3,0.1

Type RM Length L Ch R = 1 ,14032.9,410.9,430.9,450.9
XS GIS Cut Line= 3
     1937306.983      290040.009     1937789.085      290054.007
     1938033.879      290590.604
#Sta/Elev= 30
       0 2031.03    19.7 2022.58    39.4 2010.87    49.2 2007.50    78.7 1997.90
   108.3 1991.34   187.0 1967.12   265.8 1932.78   275.6 1927.03   334.7 1912.21
   354.4 1905.04   359.2 1904.92   364.2 1904.80   374.2 1906.00   423.2 1917.03
   433.1 1920.58   482.3 1929.29   542.3 1952.03   562.3 1961.60   712.2 2006.10
   772.2 2018.65   802.2 2019.53   862.2 2030.04   892.2 2036.82   912.2 2039.56
   942.2 2046.34   982.1 2068.83  1032.1 2090.17  1052.1 2096.06  1072.1 2105.75
#Mann= 3 , 0 , 0
       0     0.1       0   359.2   0.045       0   374.2     0.1       0
Bank Sta=   359.2,   374.2
Exp/Cntr=0.3,0.1

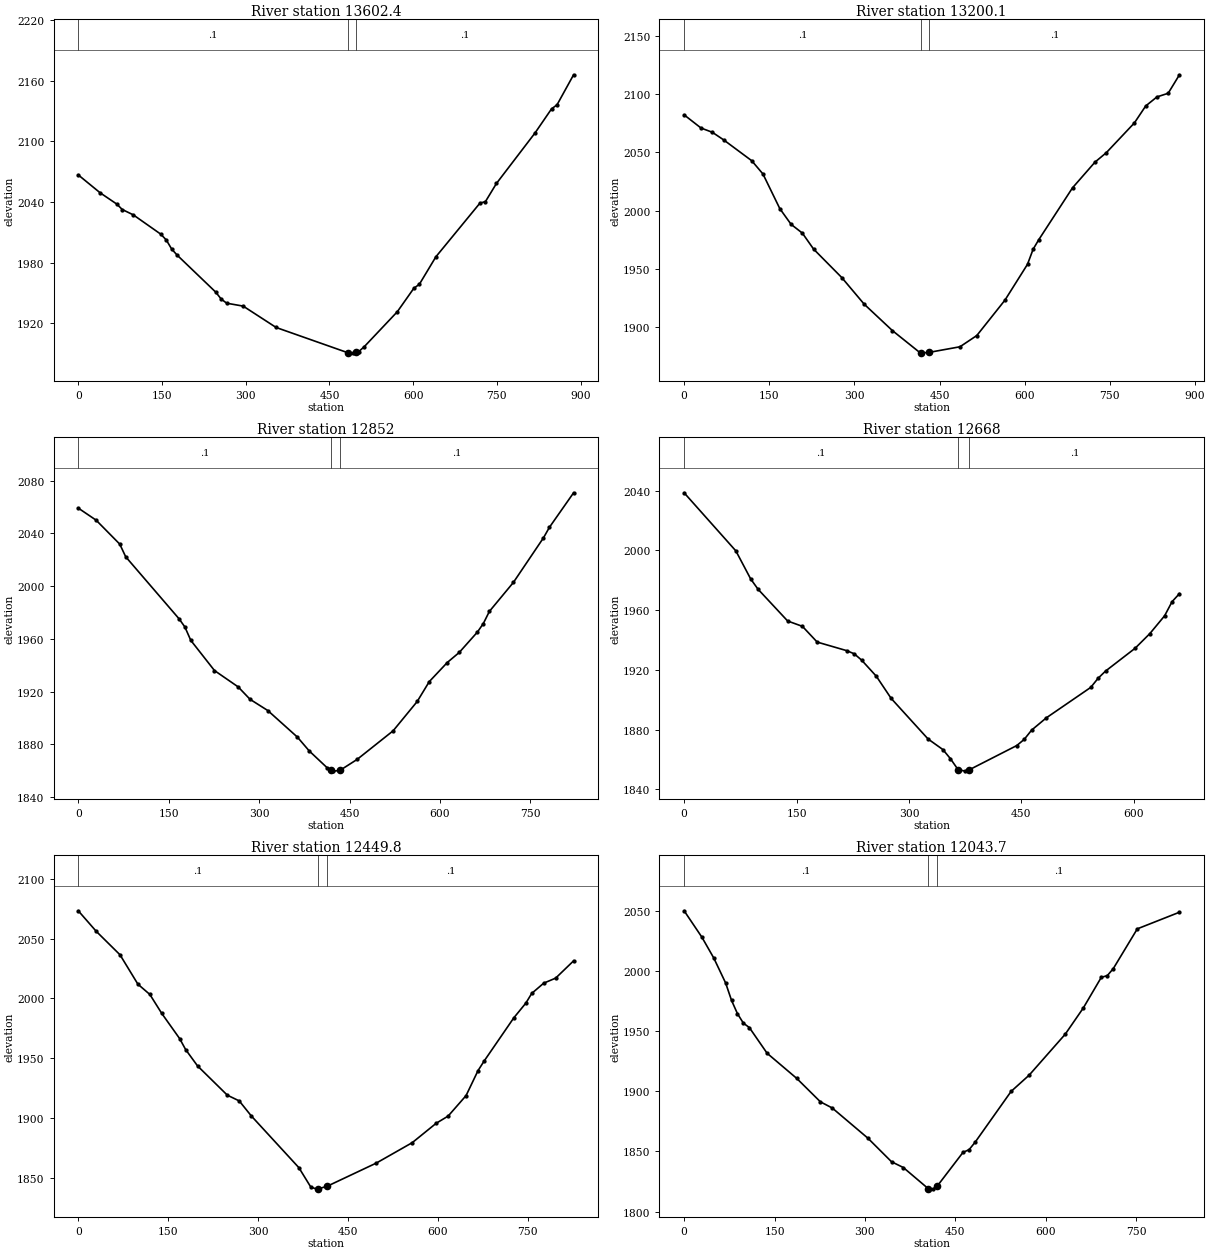
Type RM Length L Ch R = 1 ,13602.4,408.7,401.3,394.1
XS GIS Cut Line= 3
     1937267.949      290201.865     1937565.962      290354.421
     1937919.972      290778.742
#Sta/Elev= 30
       0 2066.69    39.4 2048.91    68.9 2037.90    78.8 2032.48    98.5 2027.21
   147.7 2008.13   157.6 2002.38   167.4 1993.31   177.2 1987.31   246.2 1950.79
   256.0 1943.93   265.9 1939.80   295.4 1936.93   354.5 1915.78   482.8 1890.84
   492.7 1890.42   497.8 1891.23   502.6 1891.99   512.4 1896.81   571.6 1931.38
   601.2 1954.58   611.1 1958.53   640.7 1985.72   719.6 2038.80   729.5 2040.33
   749.2 2058.26   818.3 2108.20   847.9 2132.04   857.8 2136.10   887.4 2165.74
#Mann= 3 , 0 , 0
       0     0.1       0   482.8   0.045       0   497.8     0.1       0
Bank Sta=   482.8,   497.8
Exp/Cntr=0.3,0.1

Type RM Length L Ch R = 1 ,13200.1,346.3,347.7,350
XS GIS Cut Line= 2
     1936993.578      290445.262     1937724.677      290921.343
#Sta/Elev= 30
       0 2082.36    29.7 2071.04    49.6 2067.38    69.4 2060.90   119.0 2042.91
   138.8 2031.49   168.5 2001.67   188.4 1988.12   208.2 1980.60   228.0 1966.84
   277.6 1942.35   317.2 1919.39   366.8 1896.70   416.4 1877.29   417.1 1877.31
   432.1 1877.99   485.8 1882.75   515.5 1892.44   565.1 1922.91   604.8 1953.75
   614.7 1966.72   624.6 1974.88   684.1 2019.58   723.7 2041.70   743.6 2049.80
   793.1 2075.44   813.0 2090.02   832.8 2097.81   852.6 2100.95   872.4 2116.83
#Mann= 3 , 0 , 0
       0     0.1       0   417.1   0.045       0   432.1     0.1       0
Bank Sta=   417.1,   432.1
Exp/Cntr=0.3,0.1

Type RM Length L Ch R = 1 ,12852,185.9,184,181
XS GIS Cut Line= 3
     1936871.745      290763.783     1937220.161      290984.775
     1937539.062      291240.794
#Sta/Elev= 30
       0 2059.19    29.5 2050.08    68.8 2031.86    78.6 2022.30   167.0 1975.31
   176.8 1969.04   186.6 1958.89   225.9 1935.98   265.2 1923.58   284.9 1914.16
   314.4 1905.63   363.5 1885.47   383.1 1874.99   412.6 1862.32   418.9 1860.66
   422.6 1859.68   433.9 1860.20   462.5 1868.55   522.3 1890.28   562.2 1912.51
   582.2 1927.56   612.1 1942.08   632.0 1949.73   662.0 1965.12   671.9 1971.62
   681.9 1980.83   721.8 2002.84   771.7 2036.68   781.6 2044.68   821.6 2070.80
#Mann= 3 , 0 , 0
       0     0.1       0   418.9   0.045       0   433.9     0.1       0
Bank Sta=   418.9,   433.9
Exp/Cntr=0.3,0.1

Type RM Length L Ch R = 1 ,12668,215.6,218.2,217.8
XS GIS Cut Line= 2
     1936797.427      290936.291     1937358.881      291284.829
#Sta/Elev= 30
       0 2038.53    69.0 1999.66    88.8 1980.86    98.6 1974.00   138.1 1952.74
   157.8 1949.16   177.5 1938.63   217.0 1932.88   226.9 1930.79   236.7 1926.60
   256.4 1915.77   276.2 1900.93   325.5 1873.74   345.2 1866.69   355.1 1860.70
   365.4 1853.31   374.8 1852.26   380.4 1853.15   443.8 1869.38   453.7 1873.49
   463.6 1879.70   483.3 1887.95   542.5 1908.31   552.3 1914.41   562.2 1919.21
   601.7 1934.50   621.4 1944.33   641.1 1956.27   651.0 1965.68   660.8 1971.04
#Mann= 3 , 0 , 0
       0     0.1       0   365.4   0.045       0   380.4     0.1       0
Bank Sta=   365.4,   380.4
Exp/Cntr=0.3,0.1

Type RM Length L Ch R = 1 ,12449.8,401.7,406,415.8
XS GIS Cut Line= 3
     1936645.975      291046.903     1936969.282      291295.602
     1937331.189      291505.952
#Sta/Elev= 30
       0 2073.34    29.8 2056.26    69.6 2036.53    99.5 2011.92   119.4 2003.35
   139.3 1987.46   169.1 1966.43   179.1 1957.26   199.0 1943.54   248.7 1919.06
   268.6 1914.26   288.5 1901.81   368.1 1858.40   388.0 1842.16   398.0 1840.44
   400.4 1840.66   415.4 1842.87   497.6 1862.32   557.4 1879.37   597.3 1895.57
   617.2 1901.58   647.1 1918.71   667.0 1939.56   677.0 1947.45   726.8 1983.81
   746.8 1996.07   756.7 2004.22   776.7 2012.81   796.6 2017.02   826.5 2031.46
#Mann= 3 , 0 , 0
       0     0.1       0   400.4   0.045       0   415.4     0.1       0
Bank Sta=   400.4,   415.4
Exp/Cntr=0.3,0.1

Type RM Length L Ch R = 1 ,12043.7,205.6,200.3,192.5
XS GIS Cut Line= 3
     1936495.282      291307.376     1936766.446      291618.910
     1936998.422      291955.854
#Sta/Elev= 30
       0 2050.19    29.5 2028.22    49.2 2010.90    68.8 1990.22    78.7 1975.64
    88.5 1964.60    98.3 1956.77   108.2 1953.09   137.7 1931.71   186.8 1910.84
   226.2 1891.30   245.8 1886.19   304.8 1861.16   344.2 1841.47   363.8 1836.66
   405.5 1818.96   413.0 1818.69   420.5 1821.50   462.9 1849.28   472.9 1851.48
   482.9 1857.65   542.7 1899.96   572.7 1913.51   632.5 1947.52   662.5 1969.34
   692.4 1994.84   702.4 1996.30   712.3 2002.10   752.2 2035.20   822.1 2049.02
#Mann= 3 , 0 , 0
       0     0.1       0   405.5   0.045       0   420.5     0.1       0
Bank Sta=   405.5,   420.5
Exp/Cntr=0.3,0.1

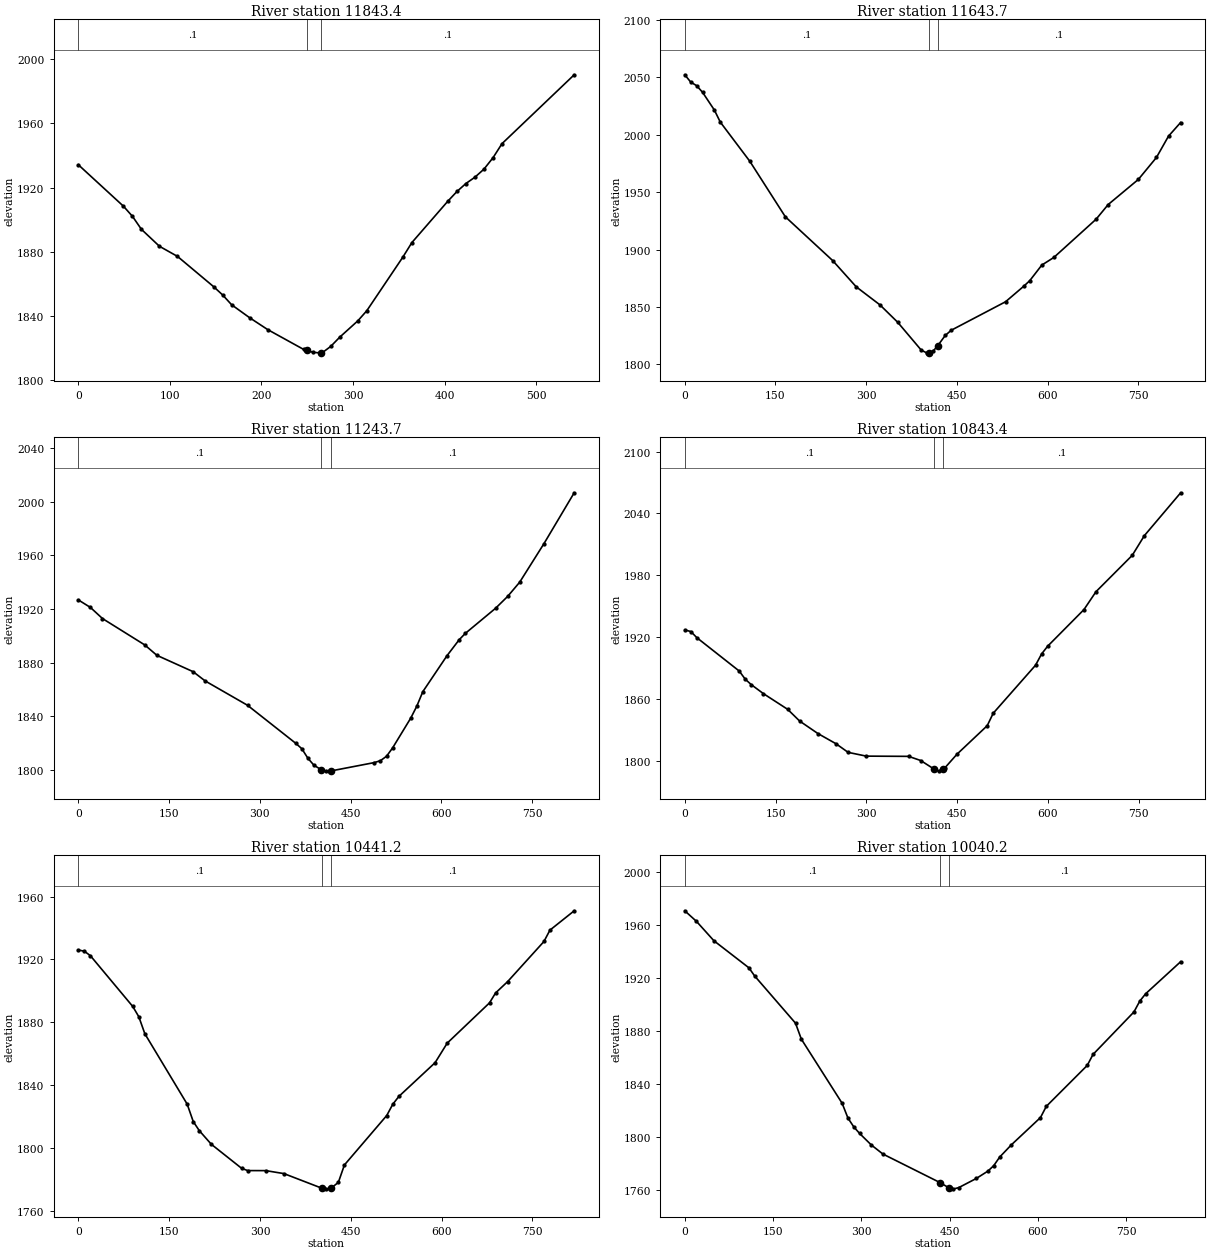
Type RM Length L Ch R = 1 ,11843.4,198.2,199.6,201.1
XS GIS Cut Line= 2
     1936413.889      291607.118     1936854.302      291922.115
#Sta/Elev= 30
       0 1934.21    49.2 1908.37    59.1 1902.03    68.9 1893.90    88.6 1883.31
   108.3 1877.00   147.7 1858.13   157.5 1852.99   167.4 1846.82   187.0 1838.75
   206.7 1831.35   246.1 1818.92   249.8 1818.27   256.0 1817.17   264.8 1816.68
   265.8 1816.62   275.7 1820.84   285.5 1826.59   305.2 1836.75   315.0 1843.06
   354.4 1876.54   364.3 1885.65   403.6 1911.50   413.5 1917.52   423.3 1922.51
   433.2 1926.47   443.0 1931.48   452.9 1938.61   462.7 1947.38   541.5 1990.35
#Mann= 3 , 0 , 0
       0     0.1       0   249.8   0.045       0   264.8     0.1       0
Bank Sta=   249.8,   264.8
Exp/Cntr=0.3,0.1

Type RM Length L Ch R = 1 ,11643.7,407.1,400,393.9
XS GIS Cut Line= 3
     1936183.136      291654.948     1936501.430      291914.644
     1936817.826      292174.252
#Sta/Elev= 30
       0 2052.28     9.8 2045.96    19.6 2042.82    29.3 2037.12    48.9 2021.60
    58.7 2011.11   107.6 1976.93   166.3 1928.61   244.5 1890.52   283.6 1867.58
   322.8 1851.87   352.1 1836.76   391.2 1812.40   401.0 1809.85   403.3 1810.27
   410.8 1811.66   418.3 1816.30   430.8 1825.26   440.7 1829.78   530.6 1854.62
   560.5 1868.07   570.5 1872.93   590.5 1886.55   610.4 1893.19   680.3 1926.50
   700.3 1939.29   750.2 1961.17   780.1 1980.28   800.1 1998.89   820.1 2010.74
#Mann= 3 , 0 , 0
       0     0.1       0   403.3   0.045       0   418.3     0.1       0
Bank Sta=   403.3,   418.3
Exp/Cntr=0.3,0.1

Type RM Length L Ch R = 1 ,11243.7,404.1,400.2,394.7
XS GIS Cut Line= 3
     1935873.923      292068.393     1936255.381      292217.012
     1936629.495      292385.103
#Sta/Elev= 30
       0 1926.81    20.0 1921.21    39.9 1912.94   109.8 1893.28   129.8 1885.55
   189.7 1873.36   209.7 1866.44   279.6 1848.34   359.5 1819.95   369.4 1815.97
   379.4 1808.88   389.4 1803.68   401.9 1800.22   409.4 1799.28   416.9 1799.37
   489.4 1805.66   499.4 1807.09   509.4 1810.36   519.4 1816.56   549.4 1838.77
   559.4 1847.63   569.4 1858.49   609.5 1885.37   629.5 1897.17   639.5 1901.84
   689.5 1920.55   709.5 1929.39   729.5 1940.04   769.5 1968.67   819.5 2006.59
#Mann= 3 , 0 , 0
       0     0.1       0   401.9   0.045       0   416.9     0.1       0
Bank Sta=   401.9,   416.9
Exp/Cntr=0.3,0.1

Type RM Length L Ch R = 1 ,10843.4,400.3,401.7,403.4
XS GIS Cut Line= 3
     1935738.918      292514.583     1936139.857      292598.716
     1936542.665      292672.279
#Sta/Elev= 30
       0 1926.89    10.0 1925.34    20.0 1919.32    89.9 1886.98    99.9 1879.02
   109.9 1873.71   129.9 1865.01   169.9 1849.79   189.8 1838.36   219.8 1826.30
   249.8 1816.35   269.8 1807.98   299.8 1804.32   369.7 1804.09   389.7 1800.06
     412 1791.66   419.7 1789.75     427 1792.07   429.6 1792.90   449.6 1806.15
   499.6 1833.88   509.5 1845.97   579.4 1892.60   589.4 1903.54   599.4 1911.08
   659.4 1946.66   679.3 1964.06   739.2 1999.37   759.2 2018.48   819.1 2060.08
#Mann= 3 , 0 , 0
       0     0.1       0     412   0.045       0     427     0.1       0
Bank Sta=     412,     427
Exp/Cntr=0.3,0.1

Type RM Length L Ch R = 1 ,10441.2,404.1,400.8,391.2
XS GIS Cut Line= 3
     1935653.857      292882.975     1936050.062      292986.474
     1936446.266      293089.973
#Sta/Elev= 30
       0 1926.01    10.0 1925.26    20.0 1922.36    89.9 1890.10    99.9 1883.57
   109.9 1872.71   179.8 1827.95   189.8 1816.90   199.8 1811.09   219.7 1802.41
   269.7 1787.14   279.7 1785.69   309.6 1785.66   339.6 1783.77     402 1774.51
   409.5 1773.89     417 1774.36   429.5 1778.18   439.5 1789.26   509.4 1820.71
   519.4 1827.87   529.4 1832.85   589.3 1854.34   609.3 1866.77   679.2 1892.40
   689.2 1898.70   709.1 1905.91   769.1 1931.44   779.0 1938.67   819.0 1950.95
#Mann= 3 , 0 , 0
       0     0.1       0     402   0.045       0     417     0.1       0
Bank Sta=     402,     417
Exp/Cntr=0.3,0.1

Type RM Length L Ch R = 1 ,10040.2,387.5,402.7,426.7
XS GIS Cut Line= 3
     1935562.437      293307.068     1935993.504      293370.020
     1936394.733      293302.990
#Sta/Elev= 30
       0 1970.80    19.8 1962.86    49.5 1948.20   108.9 1927.80   118.8 1921.57
   188.1 1886.01   198.0 1873.96   267.3 1825.56   277.2 1814.38   287.1 1807.73
   297.0 1802.78   316.8 1794.12   336.6 1787.24   433.5 1765.72   448.5 1761.80
   455.5 1760.76   465.4 1761.90   495.2 1768.79   515.0 1774.37   524.9 1778.49
   534.9 1784.91   554.7 1794.13   604.3 1814.78   614.2 1823.23   683.7 1854.11
   693.6 1862.43   763.1 1894.49   773.0 1902.65   782.9 1908.18   842.4 1932.38
#Mann= 3 , 0 , 0
       0     0.1       0   433.5   0.045       0   448.5     0.1       0
Bank Sta=   433.5,   448.5
Exp/Cntr=0.3,0.1

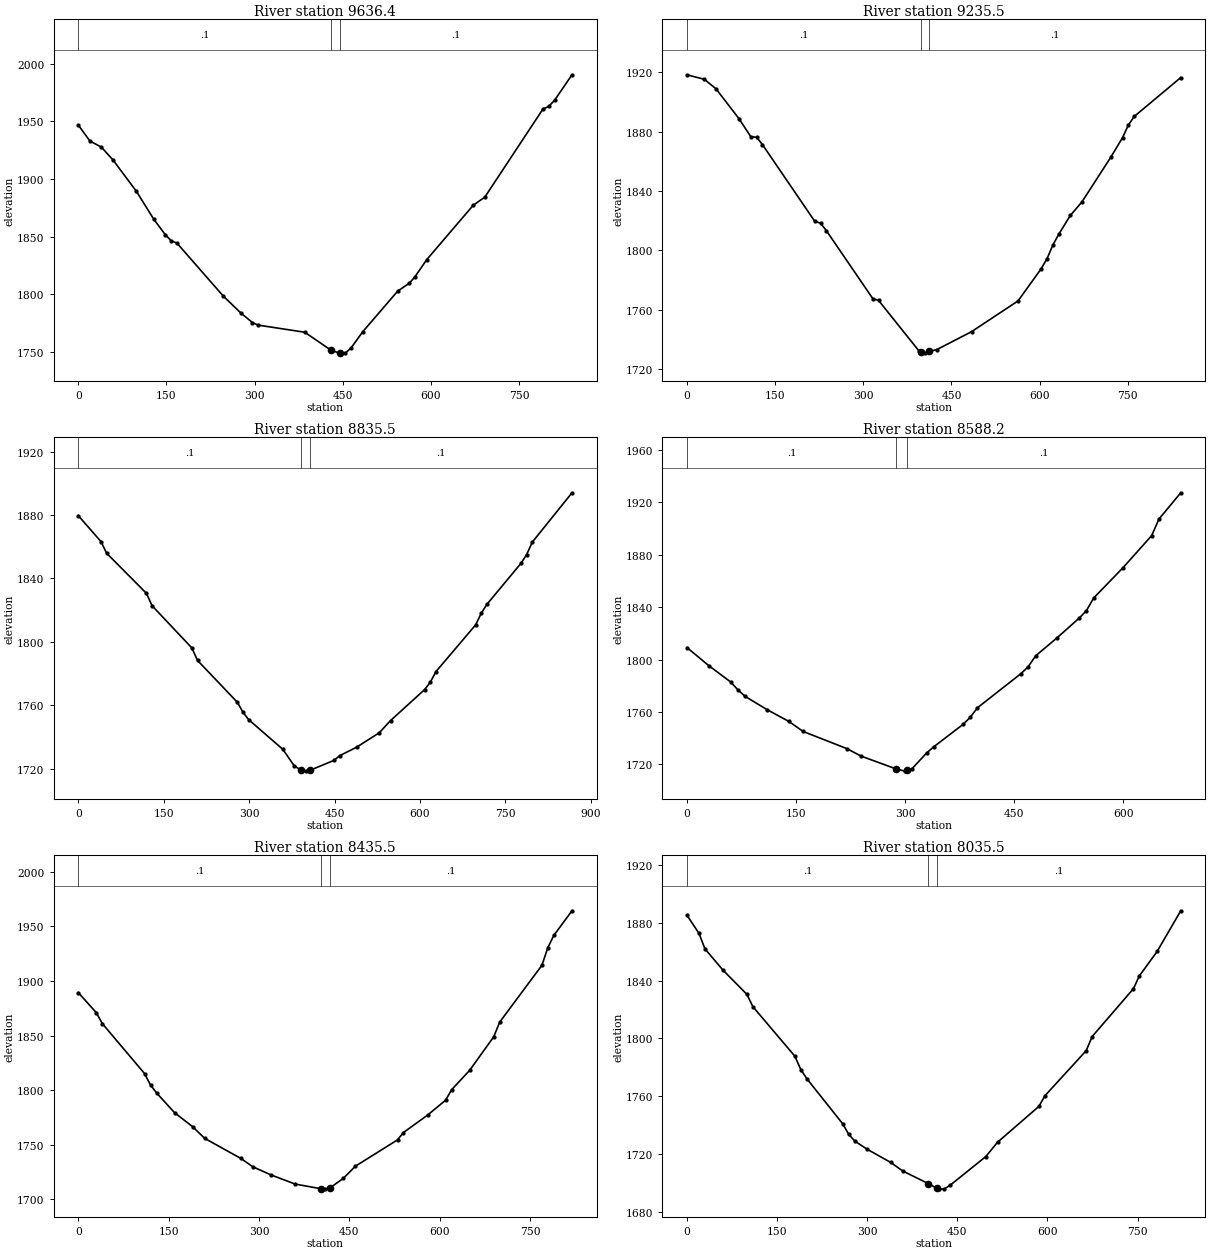
Type RM Length L Ch R = 1 ,9636.4,391.6,400.4,400.5
XS GIS Cut Line= 3
     1935514.340      293404.855     1935829.669      293704.107
     1936083.207      294019.992
#Sta/Elev= 30
       0 1946.97    19.8 1933.09    39.5 1927.68    59.3 1916.52    98.8 1889.53
   128.4 1865.31   148.2 1851.77   158.1 1846.58   168.0 1844.47   247.0 1798.45
   276.6 1783.95   296.4 1775.58   306.3 1773.42   385.3 1767.26   430.1 1751.63
   444.6 1749.15   445.1 1749.15   454.5 1749.22   464.4 1753.83   484.1 1767.80
   543.4 1802.92   563.2 1809.74   573.0 1815.51   592.8 1830.23   671.8 1877.31
   691.6 1884.43   790.4 1960.73   800.2 1963.05   810.1 1968.25   839.8 1990.43
#Mann= 3 , 0 , 0
       0     0.1       0   430.1   0.045       0   445.1     0.1       0
Bank Sta=   430.1,   445.1
Exp/Cntr=0.3,0.1

Type RM Length L Ch R = 1 ,9235.5,430.2,400,388.5
XS GIS Cut Line= 3
     1935314.533      293500.694     1935471.724      293873.949
     1935740.635      294215.845
#Sta/Elev= 30
       0 1918.41    29.6 1915.39    49.4 1908.96    88.9 1888.60   108.7 1876.63
   118.5 1876.36   128.4 1871.35   217.3 1819.69   227.2 1818.39   237.1 1813.37
   316.1 1767.54   326.0 1766.29   395.1 1732.05   397.5 1731.74   405.0 1730.79
   412.5 1731.96   424.8 1733.10   484.1 1745.25   563.2 1765.98   602.7 1787.74
   612.6 1794.53   622.5 1803.69   632.4 1810.87   652.2 1823.61   671.9 1832.72
   721.4 1863.10   741.1 1876.14   751.0 1884.60   760.9 1890.34   840.0 1916.55
#Mann= 3 , 0 , 0
       0     0.1       0   397.5   0.045       0   412.5     0.1       0
Bank Sta=   397.5,   412.5
Exp/Cntr=0.3,0.1

Type RM Length L Ch R = 1 ,8835.5,240.8,247.2,241
XS GIS Cut Line= 3
     1934839.667      294211.651     1935233.411      294146.643
     1935676.101      294297.437
#Sta/Elev= 30
       0 1879.65    39.9 1863.23    49.9 1855.86   119.7 1830.57   129.7 1822.72
   199.5 1796.10   209.5 1788.18   279.4 1761.78   289.3 1755.44   299.3 1750.80
   359.2 1732.11   379.1 1721.71   391.6 1718.84   399.1 1718.35   406.6 1718.83
   448.8 1725.12   458.8 1728.05   488.6 1733.44   528.4 1742.53   548.3 1750.28
   608.0 1769.80   618.0 1774.42   627.9 1781.14   697.6 1810.66   707.5 1818.00
   717.5 1823.66   777.2 1849.49   787.1 1855.01   797.1 1862.89   866.7 1894.00
#Mann= 3 , 0 , 0
       0     0.1       0   391.6   0.045       0   406.6     0.1       0
Bank Sta=   391.6,   406.6
Exp/Cntr=0.3,0.1

Type RM Length L Ch R = 1 ,8588.2,151.8,152.7,153.6
XS GIS Cut Line= 2
     1934974.527      294354.593     1935648.271      294437.717
#Sta/Elev= 30
       0 1809.10    30.0 1795.31    59.9 1782.96    69.9 1776.97    79.9 1771.91
   109.8 1761.89   139.8 1752.89   159.7 1745.16   219.6 1732.13   239.6 1726.34
   287.1 1716.70   299.5 1714.94   302.1 1715.44   309.5 1716.87   329.4 1728.74
   339.4 1733.56   379.4 1750.49   389.3 1755.87   399.3 1763.22   459.2 1789.27
   469.2 1794.55   479.2 1802.74   509.1 1816.69   539.1 1831.50   549.1 1837.19
   559.0 1846.82   599.0 1869.71   638.9 1894.47   648.9 1907.09   678.8 1927.04
#Mann= 3 , 0 , 0
       0     0.1       0   287.1   0.045       0   302.1     0.1       0
Bank Sta=   287.1,   302.1
Exp/Cntr=0.3,0.1

Type RM Length L Ch R = 1 ,8435.5,400.1,399.9,397.1
XS GIS Cut Line= 3
     1934847.302      294476.233     1935251.866      294542.447
     1935655.732      294609.125
#Sta/Elev= 30
       0 1889.40    30.0 1870.96    40.0 1860.94   110.0 1815.24   120.0 1804.66
   130.0 1797.46   160.0 1779.31   190.0 1766.47   210.0 1755.80   270.0 1737.44
   290.0 1729.76   320.0 1722.37   360.0 1714.00   402.4 1709.77   410.0 1709.38
   417.4 1710.40   439.9 1719.22   459.9 1730.37   529.8 1754.48   539.7 1761.22
   579.7 1777.15   609.6 1790.80   619.6 1800.40   649.6 1818.20   689.5 1848.91
   699.5 1862.40   769.4 1914.33   779.4 1930.62   789.3 1941.83   819.3 1964.22
#Mann= 3 , 0 , 0
       0     0.1       0   402.4   0.045       0   417.4     0.1       0
Bank Sta=   402.4,   417.4
Exp/Cntr=0.3,0.1

Type RM Length L Ch R = 1 ,8035.5,204.7,197.1,192.2
XS GIS Cut Line= 3
     1934789.190      294873.407     1935193.000      294937.613
     1935605.676      294953.892
#Sta/Elev= 30
       0 1885.30    20.0 1872.70    29.9 1862.03    59.8 1847.36    99.7 1830.54
   109.7 1821.99   179.5 1787.75   189.5 1778.44   199.5 1772.14   259.3 1740.88
   269.3 1733.57   279.2 1729.03   299.2 1723.47   339.1 1714.18   359.0 1708.29
   401.4 1699.56   416.4 1696.15   418.7 1695.69   428.6 1695.84   438.4 1698.49
   497.4 1718.22   517.0 1728.18   585.9 1753.00   595.7 1760.27   664.6 1791.58
   674.4 1801.30   743.2 1834.46   753.0 1843.29   782.6 1860.24   821.9 1888.36
#Mann= 3 , 0 , 0
       0     0.1       0   401.4   0.045       0   416.4     0.1       0
Bank Sta=   401.4,   416.4
Exp/Cntr=0.3,0.1