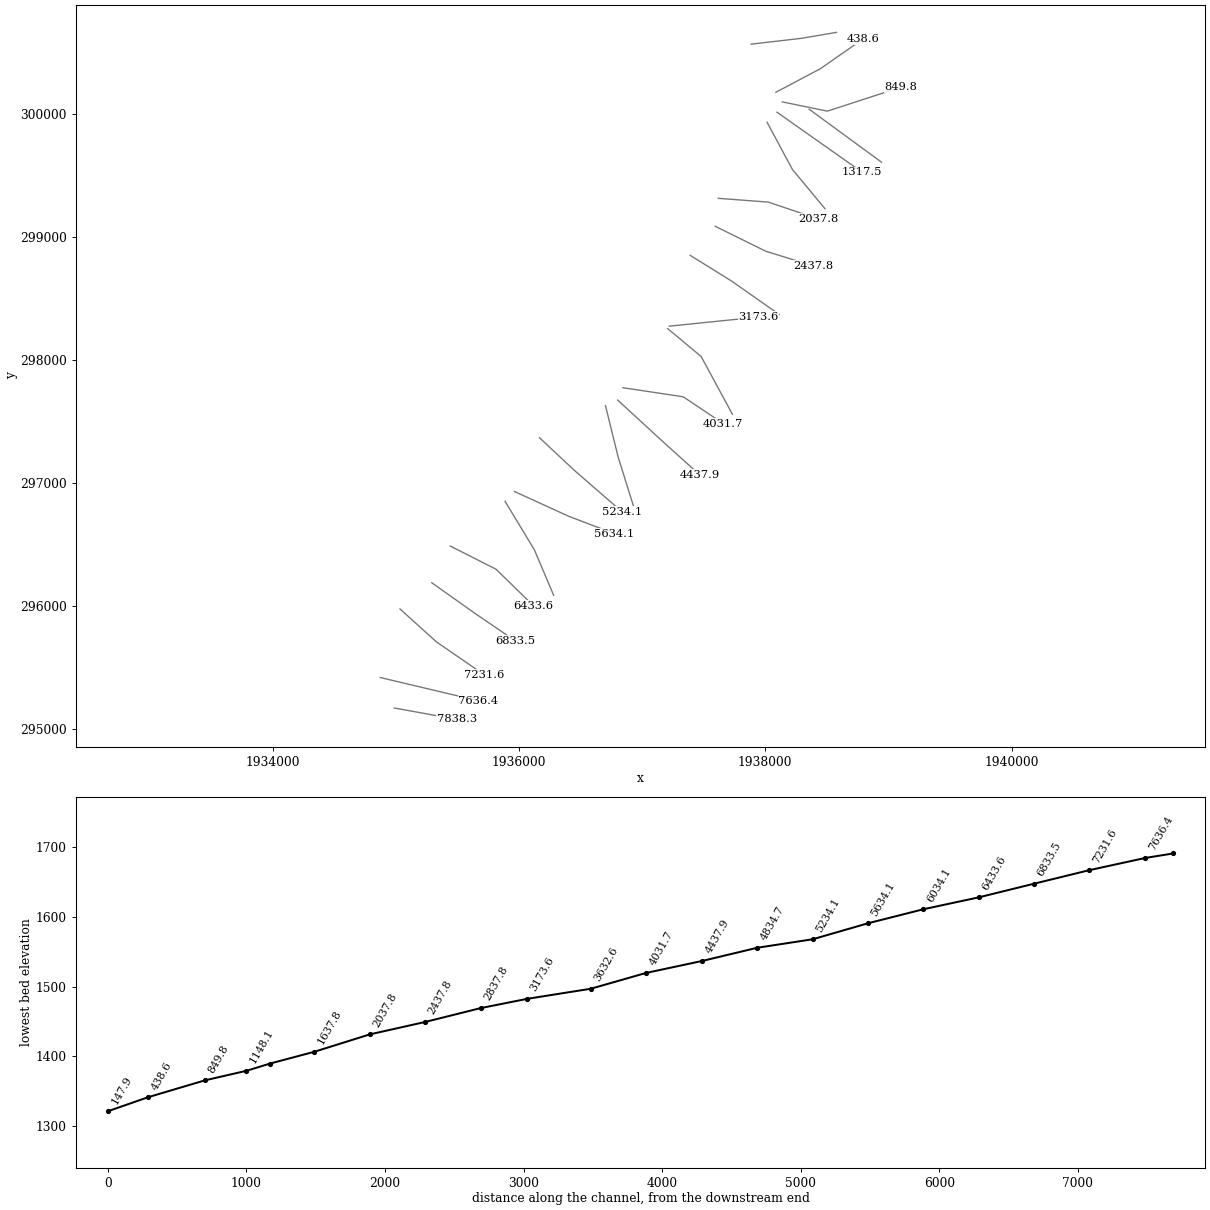
HEC-RAS study FtCrk.prj: FtCrk

--- FtCrk.g01 (geometry) --- (continued)

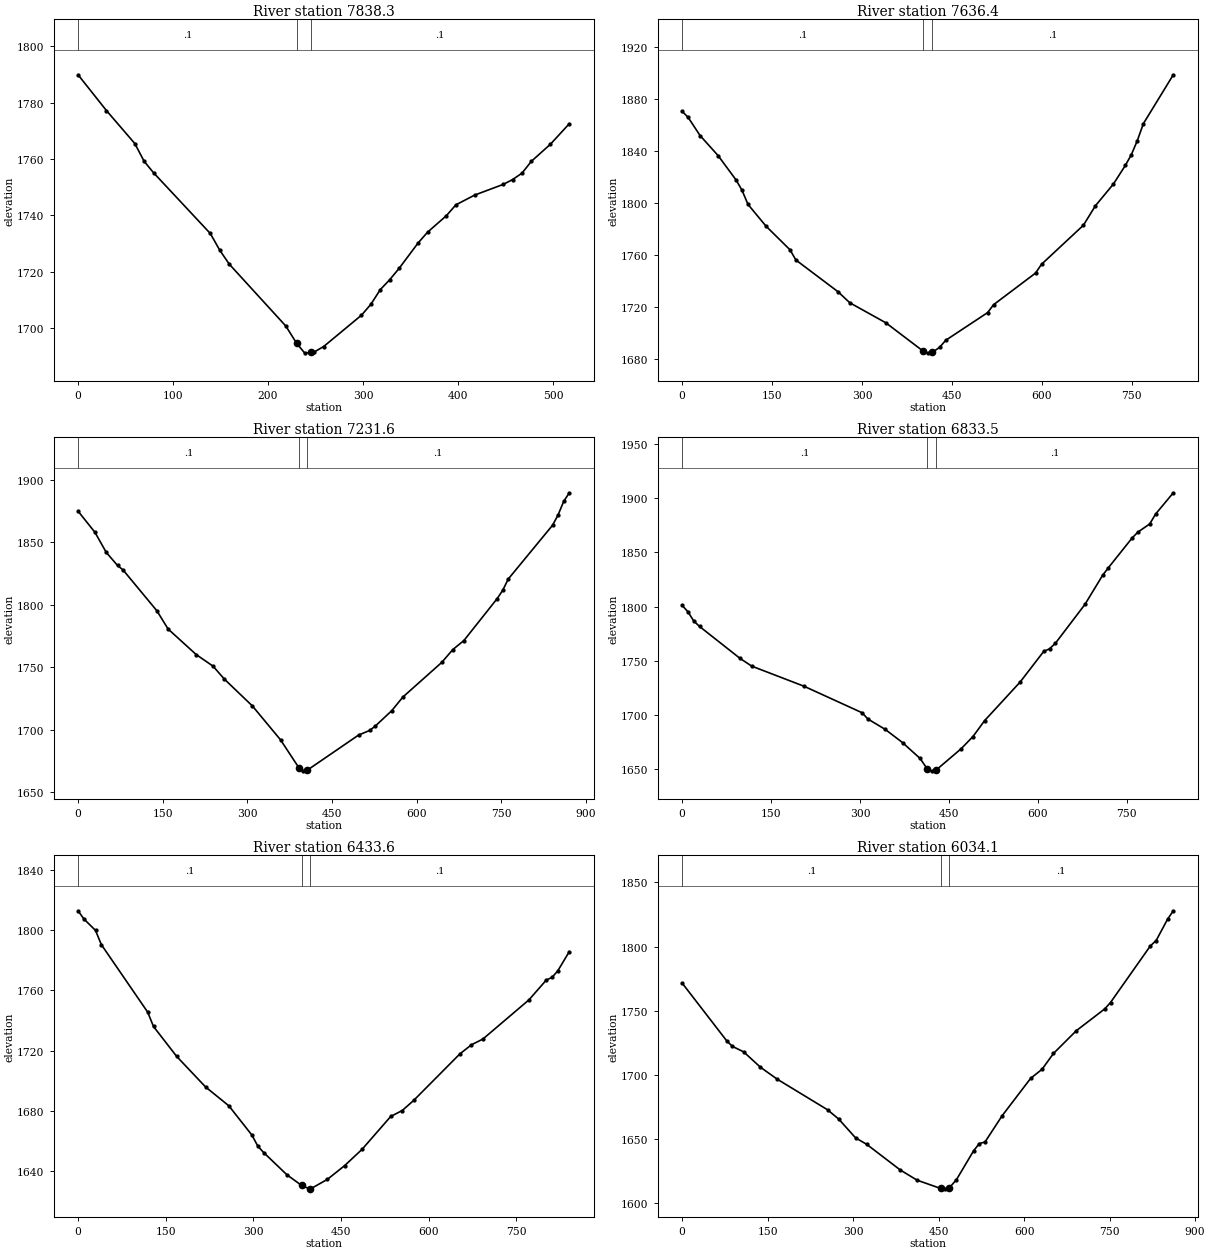
Type RM Length L Ch R = 1 ,7838.3,203.1,201.8,200.6
XS GIS Cut Line= 2
     1934987.652      295174.169     1935496.606      295082.295
#Sta/Elev= 30
       0 1789.83    29.8 1777.16    59.7 1765.44    69.6 1759.09    79.6 1755.01
   139.2 1733.50   149.2 1727.55   159.1 1722.64   218.8 1700.61   230.2 1694.46
   238.7 1691.02   245.2 1691.28   248.6 1691.42   258.6 1693.37   298.4 1704.49
   308.3 1708.36   318.3 1713.61   328.2 1717.11   338.2 1721.19   358.0 1730.12
   368.0 1733.97   387.9 1739.85   397.8 1743.67   417.7 1747.15   447.6 1750.92
   457.5 1752.64   467.4 1754.91   477.4 1759.16   497.3 1765.17   517.2 1772.46
#Mann= 3 , 0 , 0
       0     0.1       0   230.2   0.045       0   245.2     0.1       0
Bank Sta=   230.2,   245.2
Exp/Cntr=0.3,0.1

Type RM Length L Ch R = 1 ,7636.4,416.3,404.8,396.3
XS GIS Cut Line= 3
     1934873.199      295421.841     1935271.676      295327.466
     1935670.153      295233.091
#Sta/Elev= 30
       0 1870.62    10.0 1865.95    30.0 1851.93    59.9 1836.58    89.9 1817.83
    99.9 1809.86   109.9 1798.96   139.8 1782.31   179.8 1764.11   189.8 1756.18
   259.7 1731.89   279.7 1723.28   339.6 1707.93     402 1686.08   409.5 1684.56
     417 1685.05   429.5 1689.05   439.5 1694.41   509.4 1715.72   519.4 1721.82
   589.3 1746.12   599.3 1752.89   669.2 1782.97   689.2 1797.93   719.1 1814.58
   739.1 1828.97   749.1 1837.22   759.1 1848.09   769.1 1861.04   819.0 1898.65
#Mann= 3 , 0 , 0
       0     0.1       0     402   0.045       0     417     0.1       0
Bank Sta=     402,     417
Exp/Cntr=0.3,0.1

Type RM Length L Ch R = 1 ,7231.6,395.1,397.9,398.2
XS GIS Cut Line= 3
     1935033.661      295978.623     1935329.403      295711.458
     1935717.782      295444.002
#Sta/Elev= 30
       0 1874.91    29.9 1857.99    49.8 1842.02    69.8 1831.53    79.7 1827.89
   139.5 1795.31   159.4 1780.71   209.2 1760.26   239.1 1750.96   259.1 1740.62
   308.9 1719.08   358.7 1692.00     391 1669.80   398.6 1667.03     406 1667.79
   496.8 1695.86   516.4 1699.55   526.3 1702.99   555.7 1715.42   575.4 1726.32
   644.2 1753.98   663.8 1764.25   683.4 1771.46   742.4 1805.02   752.2 1811.63
   762.0 1820.66   840.6 1863.75   850.5 1872.16   860.3 1882.82   870.1 1889.61
#Mann= 3 , 0 , 0
       0     0.1       0     391   0.045       0     406     0.1       0
Bank Sta=     391,     406
Exp/Cntr=0.3,0.1

Type RM Length L Ch R = 1 ,6833.5,396.4,399.8,402.9
XS GIS Cut Line= 3
     1935291.851      296191.349     1935635.264      295947.913
     1935971.823      295718.200
#Sta/Elev= 30
       0 1801.12     9.8 1795.17    19.6 1786.65    29.4 1781.55    97.9 1751.92
   117.5 1744.82   205.6 1726.24   303.5 1701.71   313.3 1695.94   342.6 1686.28
   372.0 1673.98   401.4 1659.38   413.4 1649.81   420.9 1647.67   428.4 1648.64
   470.6 1668.37   490.5 1679.62   510.4 1694.52   570.0 1730.02   609.8 1758.39
   619.7 1760.87   629.6 1765.98   679.4 1801.92   709.2 1828.84   719.1 1835.98
   758.8 1863.28   768.8 1868.89   788.7 1876.41   798.6 1885.58   828.4 1905.21
#Mann= 3 , 0 , 0
       0     0.1       0   413.4   0.045       0   428.4     0.1       0
Bank Sta=   413.4,   428.4
Exp/Cntr=0.3,0.1

Type RM Length L Ch R = 1 ,6433.6,412.4,399.4,383.1
XS GIS Cut Line= 3
     1935442.594      296489.215     1935814.287      296300.943
     1936117.397      296004.923
#Sta/Elev= 30
       0 1812.72     9.9 1807.32    29.8 1799.72    39.7 1790.34   119.0 1745.53
   129.0 1735.98   168.6 1716.15   218.2 1695.82   257.9 1683.36   297.6 1663.81
   307.5 1656.55   317.4 1652.38   357.1 1637.65   382.5 1630.50   396.8 1628.08
   397.5 1628.21   426.5 1634.56   456.1 1643.71   485.6 1654.40   534.9 1676.32
   554.6 1680.24   574.3 1687.00   653.1 1717.78   672.8 1723.81   692.5 1727.64
   771.4 1753.68   800.9 1766.75   810.8 1768.60   820.6 1772.86   840.3 1785.65
#Mann= 3 , 0 , 0
       0     0.1       0   382.5   0.045       0   397.5     0.1       0
Bank Sta=   382.5,   397.5
Exp/Cntr=0.3,0.1

Type RM Length L Ch R = 1 ,6034.1,388.4,400,418.1
XS GIS Cut Line= 3
     1935887.214      296852.630     1936125.611      296457.668
     1936281.808      296089.042
#Sta/Elev= 30
       0 1771.62    78.5 1726.45    88.3 1722.24   108.0 1717.98   137.4 1706.02
   166.9 1696.69   255.2 1672.85   274.8 1665.60   304.3 1651.00   323.9 1645.93
   382.8 1625.94   412.3 1618.02   453.8 1611.53   461.3 1611.04   468.8 1612.05
   481.4 1618.47   511.4 1640.88   521.4 1646.57   531.4 1647.74   561.4 1668.17
   611.5 1697.35   631.5 1704.41   651.5 1716.71   691.5 1734.42   741.6 1751.49
   751.6 1756.43   821.6 1800.57   831.7 1804.71   851.7 1821.32   861.7 1827.85
#Mann= 3 , 0 , 0
       0     0.1       0   453.8   0.045       0   468.8     0.1       0
Bank Sta=   453.8,   468.8
Exp/Cntr=0.3,0.1

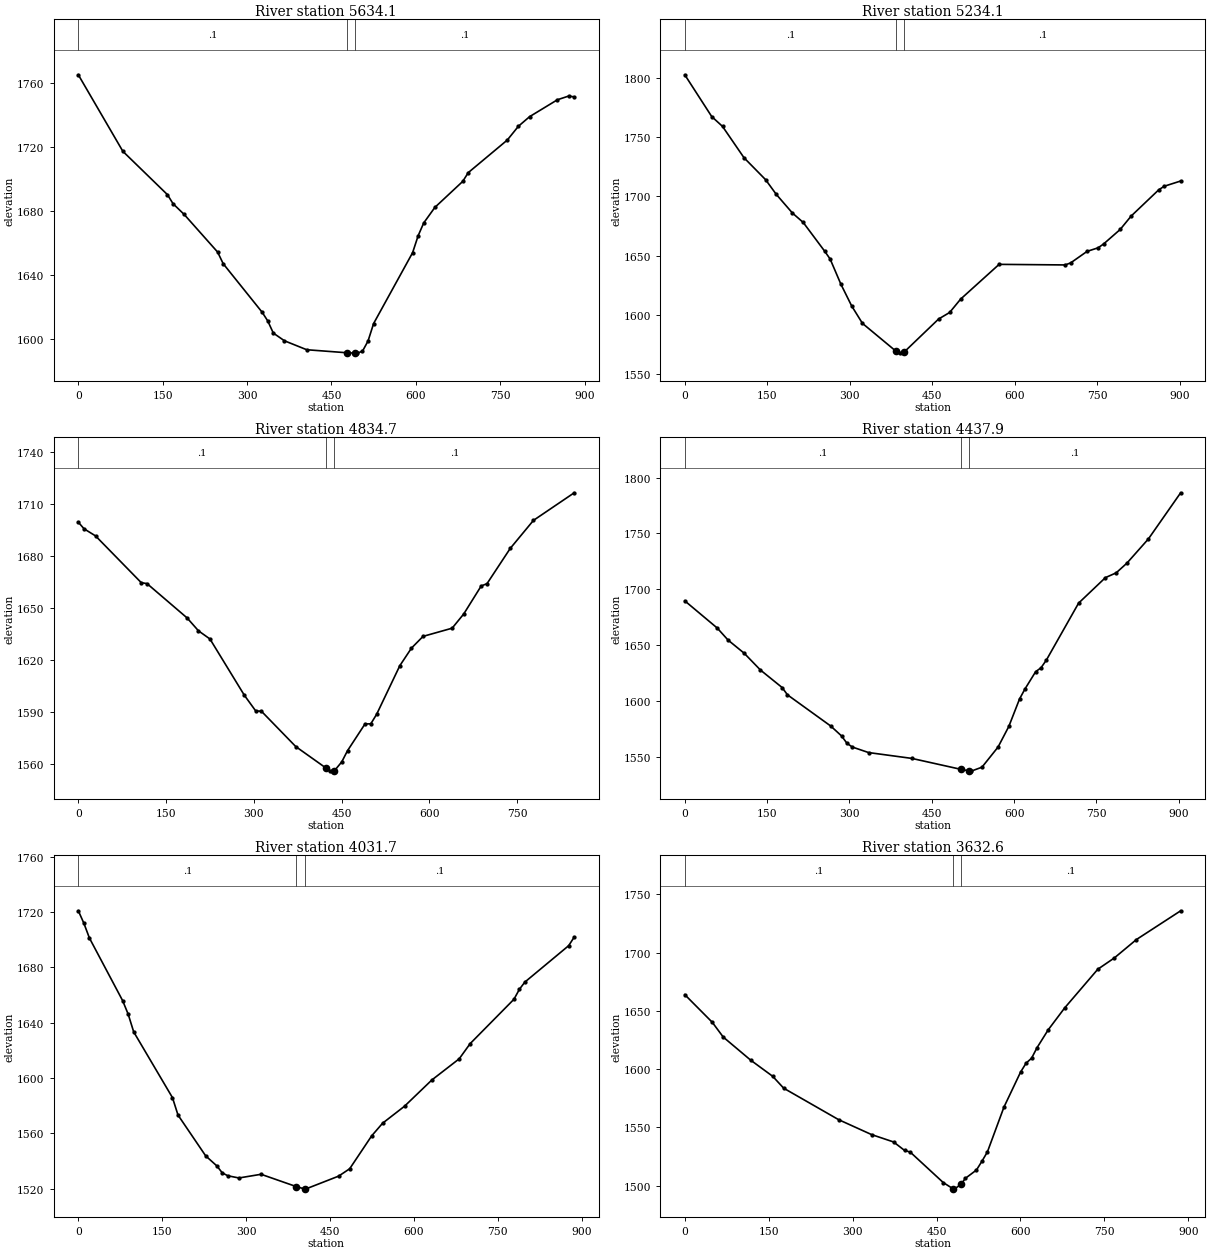
Type RM Length L Ch R = 1 ,5634.1,404.6,400,392.8
XS GIS Cut Line= 3
     1935963.614      296932.295     1936405.058      296730.820
     1936775.239      296589.799
#Sta/Elev= 30
       0 1764.83    79.2 1717.01   158.4 1689.95   168.4 1684.29   188.2 1677.57
   247.6 1654.08   257.5 1646.82   326.8 1616.46   336.7 1611.06   346.6 1603.46
   366.4 1598.64   406.0 1593.05   477.7 1591.15   492.7 1590.94   495.2 1590.93
   505.0 1592.06   515.0 1598.50   524.9 1609.42   594.2 1653.68   604.1 1664.32
   614.0 1672.29   633.8 1681.99   683.3 1698.23   693.2 1703.73   762.5 1724.06
   782.4 1732.73   802.2 1738.69   851.7 1749.26   871.5 1751.55   881.4 1751.05
#Mann= 3 , 0 , 0
       0     0.1       0   477.7   0.045       0   492.7     0.1       0
Bank Sta=   477.7,   492.7
Exp/Cntr=0.3,0.1

Type RM Length L Ch R = 1 ,5234.1,412.5,399.4,387
XS GIS Cut Line= 3
     1936166.541      297369.062     1936452.626      297101.517
     1936838.128      296767.072
#Sta/Elev= 30
       0 1802.52    49.0 1767.33    68.6 1759.06   107.7 1732.65   146.9 1714.19
   166.5 1701.73   195.8 1686.04   215.4 1678.13   254.6 1653.79   264.4 1647.28
   284.0 1626.03   303.6 1607.72   323.2 1593.05   384.2 1569.59   391.7 1567.98
   399.2 1568.96   461.7 1596.72   481.8 1602.24   501.8 1613.51   571.8 1642.79
   691.9 1642.30   701.9 1644.01   731.9 1653.75   752.0 1656.75   762.0 1660.03
   792.0 1672.17   812.0 1683.49   862.0 1705.53   872.0 1708.59   902.0 1713.02
#Mann= 3 , 0 , 0
       0     0.1       0   384.2   0.045       0   399.2     0.1       0
Bank Sta=   384.2,   399.2
Exp/Cntr=0.3,0.1

Type RM Length L Ch R = 1 ,4834.7,383.1,396.5,408.6
XS GIS Cut Line= 3
     1936702.420      297629.798     1936805.414      297211.883
     1936929.926      296813.745
#Sta/Elev= 30
       0 1699.67     9.8 1695.86    29.4 1691.77   107.6 1664.73   117.4 1664.20
   185.9 1644.37   205.4 1636.90   225.0 1632.19   283.7 1599.72   303.2 1590.62
   313.0 1590.43   371.7 1570.01   422.9 1557.72   430.4 1555.82   437.9 1556.09
   450.3 1561.16   460.2 1567.65   490.0 1583.06   500.0 1583.18   509.9 1588.64
   549.6 1616.77   569.5 1626.92   589.3 1633.70   639.0 1638.43   658.9 1646.68
   688.7 1662.84   698.6 1664.15   738.3 1684.52   778.0 1700.73   847.6 1716.66
#Mann= 3 , 0 , 0
       0     0.1       0   422.9   0.045       0   437.9     0.1       0
Bank Sta=   422.9,   437.9
Exp/Cntr=0.3,0.1

Type RM Length L Ch R = 1 ,4437.9,392.7,406.2,419.5
XS GIS Cut Line= 3
     1936801.478      297675.091     1937178.461      297328.430
     1937469.375      297066.605
#Sta/Elev= 30
       0 1689.54    59.1 1665.20    78.8 1654.43   108.3 1642.58   137.9 1627.54
   177.3 1611.90   187.1 1605.33   265.9 1577.38   285.6 1568.52   295.5 1561.90
   305.3 1558.54   334.9 1553.60   413.6 1548.37   503.1 1538.57   518.1 1537.17
   521.9 1536.96   541.5 1540.49   570.8 1558.52   590.4 1576.97   610.0 1601.64
   619.8 1610.53   639.3 1626.07   649.1 1629.58   658.9 1636.52   717.6 1687.53
   766.5 1710.39   786.1 1714.66   805.7 1723.39   844.8 1745.07   903.5 1786.37
#Mann= 3 , 0 , 0
       0     0.1       0   503.1   0.045       0   518.1     0.1       0
Bank Sta=   503.1,   518.1
Exp/Cntr=0.3,0.1

Type RM Length L Ch R = 1 ,4031.7,420.1,399.1,378.1
XS GIS Cut Line= 3
     1936844.314      297775.349     1937333.846      297701.681
     1937659.078      297484.038
#Sta/Elev= 30
       0 1720.95     9.9 1711.98    19.8 1701.29    79.2 1656.00    89.1 1646.23
    99.0 1633.38   168.3 1585.86   178.2 1573.26   227.7 1543.75   247.5 1536.56
   257.4 1531.46   267.3 1529.37   287.1 1527.79   326.7 1530.45   389.7 1521.55
   404.7 1519.82   405.9 1519.72   465.3 1529.11   485.1 1534.45   524.4 1558.23
   544.0 1567.40   583.1 1579.65   632.0 1598.64   680.9 1613.95   700.5 1624.93
   778.8 1657.02   788.6 1664.28   798.3 1669.44   876.6 1695.76   886.4 1701.90
#Mann= 3 , 0 , 0
       0     0.1       0   389.7   0.045       0   404.7     0.1       0
Bank Sta=   389.7,   404.7
Exp/Cntr=0.3,0.1

Type RM Length L Ch R = 1 ,3632.6,432.1,458.9,485.7
XS GIS Cut Line= 3
     1937208.310      298254.785     1937479.678      298028.345
     1937733.143      297559.728
#Sta/Elev= 30
       0 1663.88    49.1 1640.17    68.7 1627.50   117.8 1607.67   157.1 1593.84
   176.7 1583.65   274.9 1556.65   333.8 1543.85   373.2 1537.51   392.9 1530.21
   402.8 1528.88   462.0 1502.67   478.9 1497.54   481.7 1497.06   493.9 1501.28
   501.4 1506.29   521.2 1513.41   531.0 1520.90   540.9 1529.03   570.5 1567.49
   600.1 1597.40   610.0 1605.13   619.8 1609.36   629.7 1618.50   649.4 1633.62
   679.0 1652.52   738.2 1685.69   767.8 1695.39   807.3 1711.18   886.2 1735.78
#Mann= 3 , 0 , 0
       0     0.1       0   478.9   0.045       0   493.9     0.1       0
Bank Sta=   478.9,   493.9
Exp/Cntr=0.3,0.1

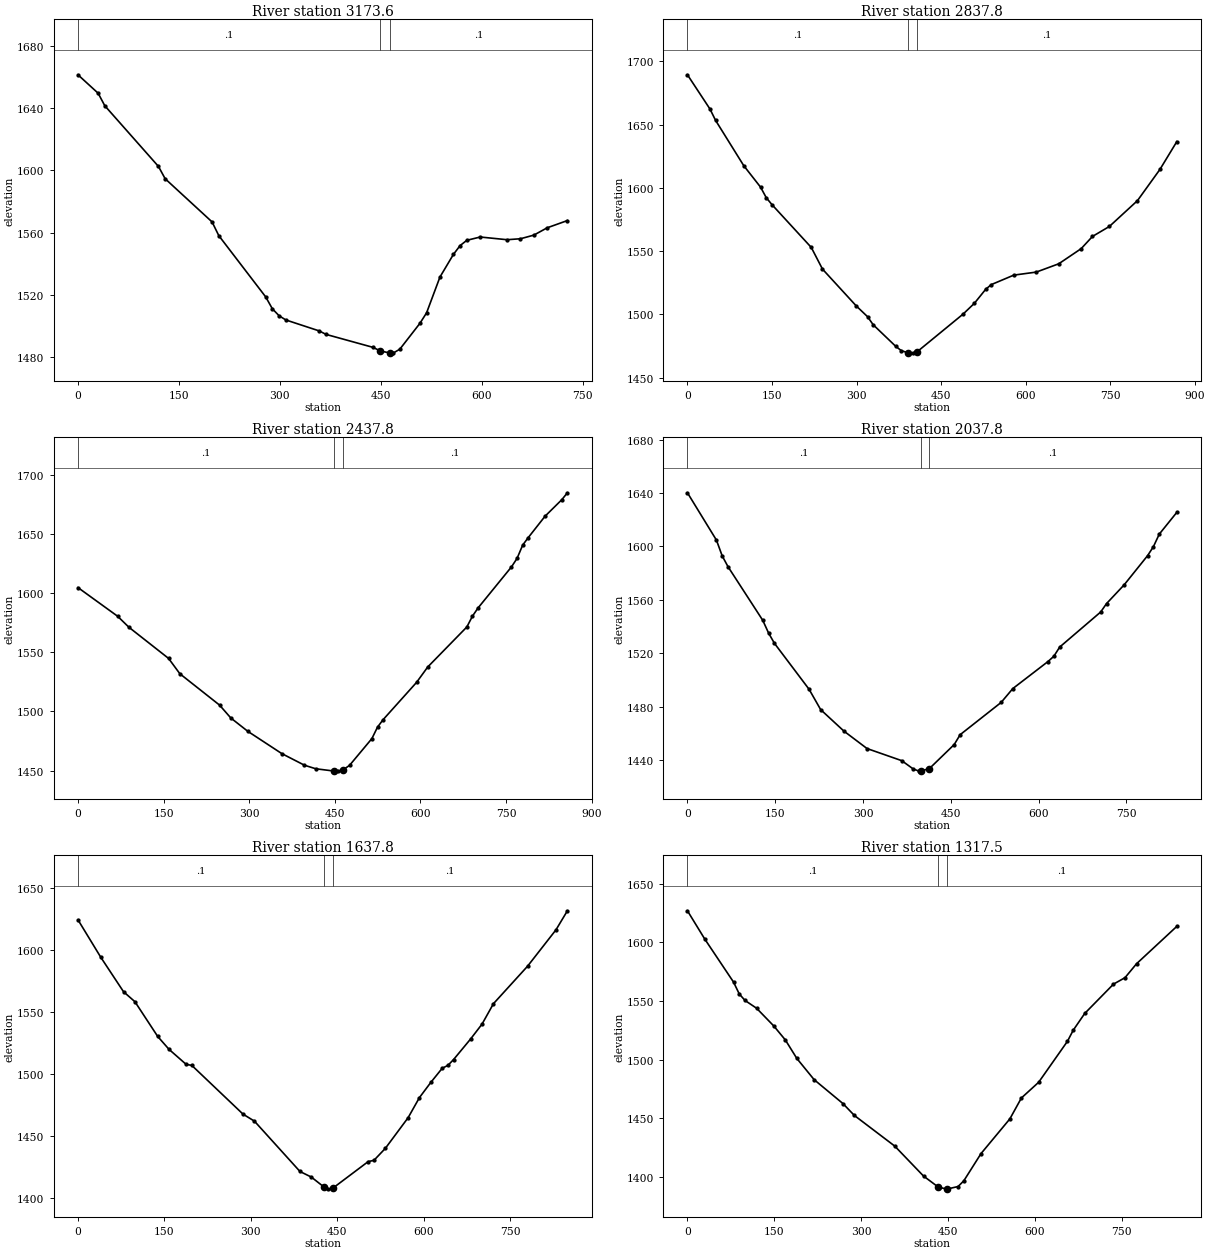
Type RM Length L Ch R = 1 ,3173.6,350.7,335.8,319.6
XS GIS Cut Line= 2
     1937221.069      298275.287     1937944.396      298349.175
#Sta/Elev= 30
       0 1661.41    29.9 1649.59    39.8 1641.54   119.5 1602.57   129.5 1594.64
   199.2 1566.90   209.2 1558.08   278.9 1518.71   288.8 1511.07   298.8 1506.61
   308.8 1503.92   358.6 1496.85   368.5 1494.65   438.2 1486.33   449.3 1484.00
   464.3 1482.62   468.1 1482.61   478.1 1485.11   508.0 1501.74   517.9 1508.48
   537.8 1531.51   557.8 1546.05   567.7 1551.69   577.7 1555.09   597.6 1557.21
   637.4 1555.48   657.4 1556.09   677.3 1558.43   697.2 1563.15   727.1 1567.77
#Mann= 3 , 0 , 0
       0     0.1       0   449.3   0.045       0   464.3     0.1       0
Bank Sta=   449.3,   464.3
Exp/Cntr=0.3,0.1

Type RM Length L Ch R = 1 ,2837.8,397.8,400,407
XS GIS Cut Line= 3
     1937390.333      298850.466     1937729.181      298639.627
     1938112.755      298370.618
#Sta/Elev= 30
       0 1689.27    39.9 1662.25    49.9 1653.23    99.8 1617.47   129.7 1600.44
   139.7 1592.17   149.7 1586.73   219.5 1552.86   239.4 1535.72   299.3 1506.61
   319.3 1498.11   329.2 1491.78   369.2 1474.71   379.1 1471.28   391.6 1469.50
   399.1 1469.32   406.6 1470.18   488.8 1500.22   508.7 1508.71   528.7 1519.75
   538.6 1523.46   578.5 1530.96   618.4 1533.36   658.3 1539.93   698.1 1551.92
   718.1 1561.56   748.0 1569.42   797.8 1589.83   837.7 1614.54   867.6 1636.49
#Mann= 3 , 0 , 0
       0     0.1       0   391.6   0.045       0   406.6     0.1       0
Bank Sta=   391.6,   406.6
Exp/Cntr=0.3,0.1

Type RM Length L Ch R = 1 ,2437.8,391.3,399.8,399.2
XS GIS Cut Line= 3
     1937594.408      299086.004     1938003.519      298884.001
     1938386.685      298764.909
#Sta/Elev= 30
       0 1604.82    69.4 1580.58    89.3 1571.22   158.7 1544.89   178.5 1531.89
   248.0 1505.38   267.8 1494.45   297.6 1483.15   357.1 1464.32   396.8 1454.48
   416.6 1451.48   448.8 1449.53   456.3 1449.48   463.8 1450.35   475.8 1454.37
   515.0 1477.04   524.8 1486.71   534.6 1493.03   593.3 1524.63   612.8 1537.62
   681.4 1571.52   691.1 1580.58   700.9 1587.55   759.6 1622.38   769.4 1629.61
   779.2 1640.79   789.0 1647.18   818.4 1665.24   847.7 1679.20   857.5 1685.04
#Mann= 3 , 0 , 0
       0     0.1       0   448.8   0.045       0   463.8     0.1       0
Bank Sta=   448.8,   463.8
Exp/Cntr=0.3,0.1

Type RM Length L Ch R = 1 ,2037.8,422.6,400.2,388.9
XS GIS Cut Line= 3
     1937618.757      299313.346     1938023.420      299282.868
     1938431.388      299145.959
#Sta/Elev= 30
       0 1640.17    49.5 1604.75    59.4 1592.88    69.3 1584.81   128.7 1544.62
   138.6 1535.12   148.5 1527.48   207.8 1492.98   227.6 1477.74   267.2 1461.70
   306.8 1448.59   366.2 1439.49   386.0 1433.21   395.9 1431.67   398.3 1431.71
   413.3 1433.55   455.8 1451.60   465.9 1458.96   535.9 1483.12   555.9 1493.52
   616.0 1513.78   626.0 1517.72   636.0 1524.62   706.0 1550.88   716.0 1557.18
   746.1 1571.22   786.1 1593.07   796.1 1599.83   806.1 1609.21   836.1 1625.54
#Mann= 3 , 0 , 0
       0     0.1       0   398.3   0.045       0   413.3     0.1       0
Bank Sta=   398.3,   413.3
Exp/Cntr=0.3,0.1

Type RM Length L Ch R = 1 ,1637.8,310,320.2,324.8
XS GIS Cut Line= 3
     1938014.775      299931.008     1938220.226      299548.117
     1938485.042      299228.994
#Sta/Elev= 30
       0 1623.91    39.5 1593.77    79.0 1565.96    98.8 1557.90   138.3 1529.89
   158.0 1519.46   187.6 1507.41   197.5 1506.54   286.4 1467.22   306.2 1461.57
   385.2 1420.98   404.9 1416.48     427 1408.41   434.5 1406.76     442 1407.46
   503.6 1428.98   513.5 1429.96   533.3 1439.62   572.8 1464.34   592.5 1480.59
   612.2 1492.81   632.0 1504.22   641.9 1506.56   651.8 1511.30   681.4 1527.92
   701.1 1539.84   720.9 1556.30   780.1 1586.53   829.5 1615.93   849.2 1631.21
#Mann= 3 , 0 , 0
       0     0.1       0     427   0.045       0     442     0.1       0
Bank Sta=     427,     442
Exp/Cntr=0.3,0.1

Type RM Length L Ch R = 1 ,1317.5,169.7,169.5,169.3
XS GIS Cut Line= 2
     1938095.341      300012.594     1938786.430      299525.656
#Sta/Elev= 30
       0 1626.81    29.8 1602.84    79.6 1566.12    89.5 1556.01    99.5 1550.46
   119.4 1543.86   149.2 1528.72   169.1 1516.85   189.0 1501.08   218.8 1483.05
   268.5 1462.72   288.4 1452.54   358.1 1426.47   407.8 1400.96   432.9 1391.71
   447.6 1389.82   447.9 1389.83   467.5 1392.03   477.4 1396.89   507.2 1420.13
   557.0 1449.66   576.9 1467.45   606.7 1480.81   656.4 1515.67   666.4 1525.12
   686.3 1539.42   736.0 1564.39   755.9 1569.89   775.8 1581.73   845.4 1613.57
#Mann= 3 , 0 , 0
       0     0.1       0   432.9   0.045       0   447.9     0.1       0
Bank Sta=   432.9,   447.9
Exp/Cntr=0.3,0.1

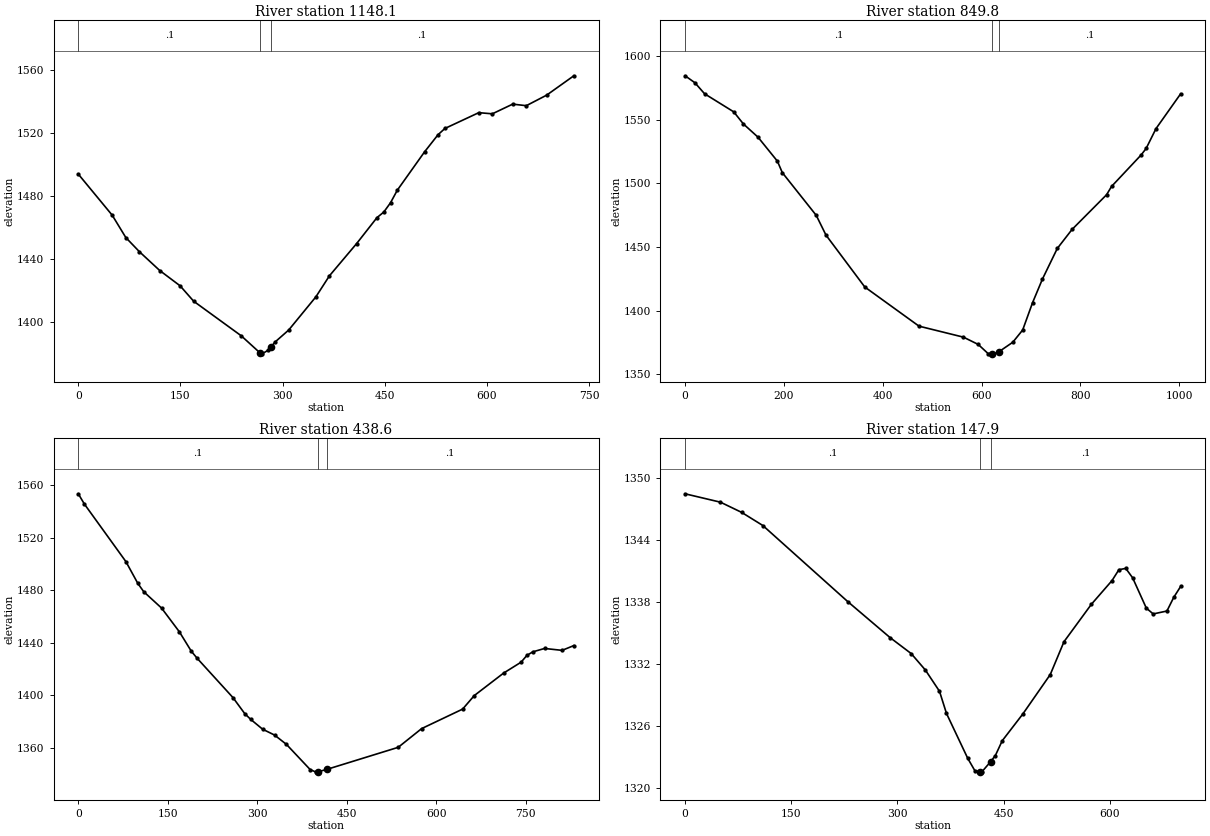
Type RM Length L Ch R = 1 ,1148.1,276.8,298.3,319.7
XS GIS Cut Line= 2
     1938356.615      300036.938     1938943.832      299607.220
#Sta/Elev= 30
       0 1493.77    49.8 1467.69    69.8 1453.49    89.7 1444.53   119.6 1432.57
   149.5 1422.86   169.4 1413.08   239.2 1391.15   267.5 1380.02   269.1 1379.49
   279.1 1382.05   282.5 1383.82   289.1 1387.25   309.0 1394.81   348.9 1415.87
   368.8 1429.23   408.7 1449.68   438.6 1466.17   448.6 1469.69   458.5 1475.61
   468.5 1483.61   508.4 1507.88   528.3 1518.82   538.3 1522.76   588.1 1532.81
   608.0 1532.08   637.9 1538.23   657.9 1537.24   687.8 1543.94   727.6 1556.20
#Mann= 3 , 0 , 0
       0     0.1       0   267.5   0.045       0   282.5     0.1       0
Bank Sta=   267.5,   282.5
Exp/Cntr=0.3,0.1

Type RM Length L Ch R = 1 ,849.8,406.5,411,418.3
XS GIS Cut Line= 3
     1938138.589      300096.594     1938504.391      300021.383
     1939103.156      300216.251
#Sta/Elev= 30
       0 1584.42    19.7 1578.98    39.3 1570.32    98.3 1556.13   117.9 1546.61
   147.4 1536.26   186.7 1517.40   196.6 1508.42   265.4 1474.82   285.0 1459.38
   363.6 1418.60   473.4 1387.84   563.4 1379.20   593.3 1373.48   613.3 1366.29
   620.4 1366.00   623.3 1365.88   635.4 1367.80   663.3 1375.22   683.3 1384.84
   703.3 1406.29   723.3 1424.83   753.3 1448.83   783.2 1463.77   853.2 1491.06
   863.2 1497.56   923.2 1522.32   933.2 1527.36   953.2 1542.96  1003.1 1570.29
#Mann= 3 , 0 , 0
       0     0.1       0   620.4   0.045       0   635.4     0.1       0
Bank Sta=   620.4,   635.4
Exp/Cntr=0.3,0.1

Type RM Length L Ch R = 1 ,438.6,298.2,290.7,280.8
XS GIS Cut Line= 3
     1938086.097      300174.632     1938447.457      300365.858
     1938793.578      300607.296
#Sta/Elev= 30
       0 1553.44    10.0 1545.77    79.8 1501.86    99.7 1485.35   109.7 1478.95
   139.6 1466.51   169.5 1448.41   189.5 1433.66   199.4 1428.23   259.3 1398.39
   279.2 1386.12   289.2 1381.76   309.1 1374.31   329.1 1369.87   349.0 1362.78
   388.9 1343.55   398.9 1341.67   401.3 1341.85   416.3 1343.70   536.4 1360.54
   575.7 1374.79   644.4 1389.62   664.0 1399.93   713.1 1417.02   742.5 1425.34
   752.3 1430.56   762.2 1433.21   781.8 1435.77   811.2 1434.33   830.8 1437.94
#Mann= 3 , 0 , 0
       0     0.1       0   401.3   0.045       0   416.3     0.1       0
Bank Sta=   401.3,   416.3
Exp/Cntr=0.3,0.1

Type RM Length L Ch R = 1 ,147.9,148.2,147.8,147.1
XS GIS Cut Line= 3
     1937884.703      300565.373     1938291.371      300612.477
     1938578.279      300661.099
#Sta/Elev= 30
       0 1348.49    49.9 1347.68    79.9 1346.69   109.8 1345.42   229.7 1338.06
   289.6 1334.57   319.5 1333.02   339.5 1331.43   359.5 1329.37   369.4 1327.22
   399.4 1322.88   409.4 1321.69   416.7 1321.58   419.1 1321.54   431.7 1322.55
   438.5 1323.15   448.2 1324.58   477.3 1327.17   516.1 1330.99   535.5 1334.17
   574.3 1337.80   603.4 1340.09   613.1 1341.14   622.8 1341.27   632.5 1340.36
   651.9 1337.42   661.6 1336.86   681.0 1337.14   690.7 1338.47   700.4 1339.52
#Mann= 3 , 0 , 0
       0     0.1       0   416.7   0.045       0   431.7     0.1       0
Bank Sta=   416.7,   431.7
Exp/Cntr=0.3,0.1